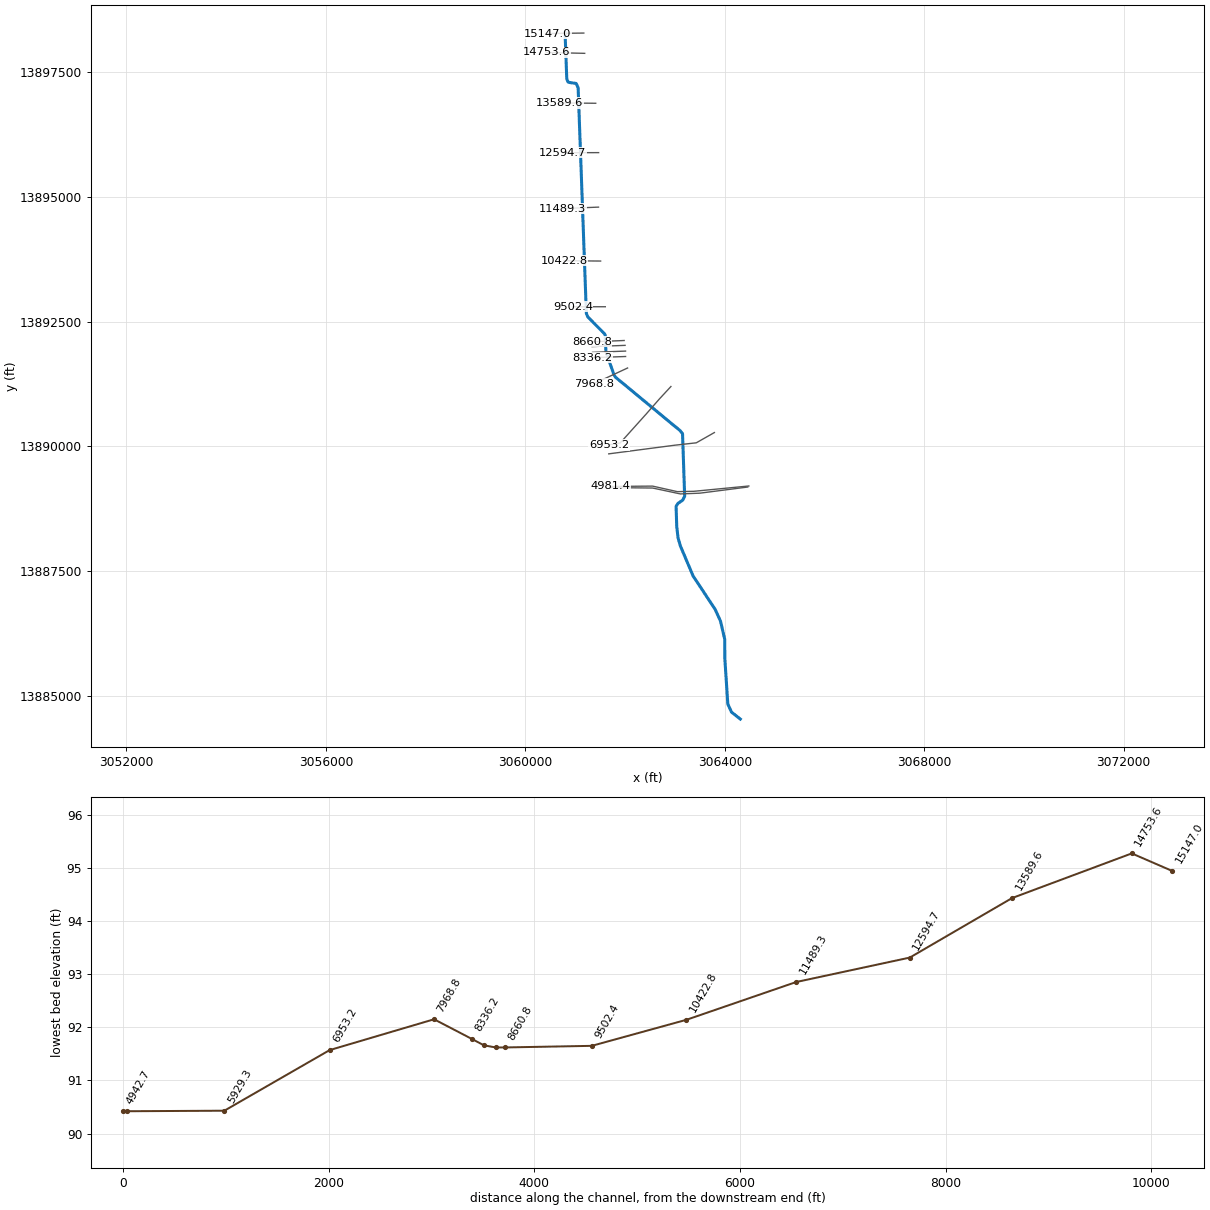
--- E141-00-00.prj (project) ---

Proj Title=E141-00-00
Current Plan=p02
Default Exp/Contr=.3,.1
English Units
Geom File=g01
Flow File=f01
Flow File=f04
Flow File=f02
Plan File=p01
Plan File=p04
Plan File=p02
Y Axis Title=Elevation
X Axis Title(PF)=Main Channel Distance
X Axis Title(XS)=Station
BEGIN DESCRIPTION:
White Oak Bayou Watershed
Beltway Channel
HCFCD Unit E141-00-00
Flood Hazard Model
10, 2, 1, 0.2%
Filename E141-00-00
Prepared by:  HALFF ASSOCIATES  DATE:  March 25, 2004
Reviewed by:  _____________________  DATE:  __________________
STATUS (FINAL)
END DESCRIPTION:
DSS Export Rating Curves= 0
DSS Export Rating Curve Sorted= 0
DSS Export Volume Flow Curves= 0
DXF OffsetX= 0
DXF OffsetY= 0
DXF ScaleX= 1
DXF ScaleY= 10

--- E141-00-00.p02 (plan) ---

Plan Title=Floodway
Version=Version 3.0.1  Mar 2001
Short Identifier=Floodway0607
Geom File=g01
Flow File=f02
Subcritical Flow
K Sum by GR= 0
Std Step Tol= 0.01
Critical Tol= 0.01
Num of Std Step Trials= 20
Max Error Tol= 0.3
Flow Tol Ratio= 0.001
Split Flow NTrial= 30
Split Flow Tol= 0.02
Split Flow Ratio= 0.02
Log Output Level= 0
Friction Slope Method= 1
Unsteady Friction Slope Method= 2
Parabolic Critical Depth
Global Vel Dist= 0 , 0 , 0
Global Log Level= 0
CheckData=True
Encroach Param=-1 ,0,0, 2
Encroach River=E141-00-00
Encroach Reach=Reach - 1
Encroach Node=15147.0
       1  4928.8  5066.5
Encroach Node=14753.6
       1  4927.8  5066.7
Encroach Node=13589.6
       1    4930  5073.1
Encroach Node=12594.7
       1  4927.9  5071.6
Encroach Node=11489.3
       1  4929.5  5070.9
Encroach Node=10422.8
       1  4929.2    5067
Encroach Node=9502.4
       1  4930.8  5066.5
Encroach Node=8660.8
       1 4927.25 5072.75
Encroach Node=8567.3
       1  4925.3  5070.8
Encroach Node=8510.3
       1  4925.3  5070.8
Encroach Node=8453.4
       1  4925.3  5070.8
Encroach Node=8336.2
       1 4927.25 5072.75
Encroach Node=7968.8
       1  4937.5  5063.2
Encroach Node=6953.2
       1  4936.2  5061.2
Encroach Node=5929.3
       1  4941.4  5061.8
Encroach Node=4981.4
       1 4944.15 5055.85
Encroach Node=4942.7
       1  4940.5  5055.5
Encroach Node=4914.2
       1  4940.5  5055.5
Encroach Node=4885.8
       1  4940.5  5055.5
Encroach Node=4850.0
       1 4944.15 5055.85
Encroach Node=4061.8
       1    4947  5050.5
Encroach Node=3448.9
       1 4952.75 5047.25
Encroach Node=3363.9
       1  4932.8  5053.8
Encroach Node=3335.4
       1  4932.8  5053.8
Encroach Node=3307.0
       1  4932.8  5053.8
Encroach Node=3225.6
       1 4952.75 5047.25
Encroach Node=2497.8
       1    4946    5053
Encroach Node=1792.4
       1 4952.55 5047.45
Encroach Node=1606.8
       1  4958.7  5053.6
Encroach Node=1578.3
       1  4958.7  5053.6
Encroach Node=1549.9
       1  4958.7  5053.6
Encroach Node=1360.6
       1 4952.55 5047.45
Encroach Node=1071.4
       1  4911.9  5059.4
Encroach Node=429.5
       1  4949.2  5064.6
Encroach Node=295.4
       1  4939.9  5064.3
Encroach Node=288.4
       1  4939.9  5064.3
Encroach Node=281.3
       1 4940.25 5064.85
Encroach Reach=E141-00-00_0003
Encroach Node=15147.0
       1  4928.8  5066.5
Encroach Node=14753.6
       1  4927.8  5066.7
Encroach Node=13589.6
       1    4930  5073.1
Encroach Node=12594.7
       1  4927.9  5071.6
Encroach Node=11489.3
       1  4929.5  5070.9
Encroach Node=10422.8
       1  4929.2    5067
Encroach Node=9502.4
       1  4930.8  5066.5
Encroach Node=8660.8
       1 4927.25 5072.75
Encroach Node=8567.3
       1  4925.3  5070.8
Encroach Node=8510.3
       1  4925.3  5070.8
Encroach Node=8453.4
       1  4925.3  5070.8
Encroach Node=8336.2
       1 4927.25 5072.75
Encroach Node=7968.8
       1  4937.5  5063.2
Encroach Node=6953.2
       1  4936.2  5061.2
Encroach Node=5929.3
       1  4941.4  5061.8
Encroach Node=4981.4
       1 4944.15 5055.85
Encroach Node=4942.7
       1  4940.5  5055.5
Encroach Node=4914.2
       1  4940.5  5055.5
Encroach Node=4885.8
       1  4940.5  5055.5
Encroach Node=4850.0
       1 4944.15 5055.85
Encroach Node=4061.8
       1    4947  5050.5
Encroach Node=3448.9
       1 4952.75 5047.25
Encroach Node=3363.9
       1  4932.8  5053.8
Encroach Node=3335.4
       1  4932.8  5053.8
Encroach Node=3307.0
       1  4932.8  5053.8
Encroach Node=3225.6
       1 4952.75 5047.25
Encroach Node=2497.8
       1    4946    5053
Encroach Node=1792.4
       1 4952.55 5047.45
Encroach Node=1606.8
       1  4958.7  5053.6
Encroach Node=1578.3
       1  4958.7  5053.6
Encroach Node=1549.9
       1  4958.7  5053.6
Encroach Node=1360.6
       1 4952.55 5047.45
Encroach Node=1071.4
       1  4911.9  5059.4
Encroach Node=429.5
       1  4949.2  5064.6
Encroach Node=295.4
       1  4939.9  5064.3
Encroach Node=288.4
       1  4939.9  5064.3
Encroach Node=281.3
       1 4940.25 5064.85
Computation Interval=1HOUR
Output Interval=1HOUR
Run HTab= 0
Run UNet= 0
Run PostProcess= 0
UNET Theta= 1
UNET ZTol= 0.02
UNET ZSATol= 0.1
UNET MxIter= 20
UNET MaxInSteps= 20
UNET DtIC= 0
UNET DtMin= 0
UNET MaxCRTS= 20
UNET WFStab= 2
UNET SFStab= 1
UNET WFX= 1
UNET SFX= 1
UNET Convert EG Bridges=-1
UNET Use Existing IB Tables=-1
Instantaneous Interval=1HOUR
Write IC File= 0
IC Time=0
Write Velocity= 0
Write Detailed= 0

--- E141-00-00.p01 (plan) ---

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Plan Title=FEMA Effective June 2007
Short Identifier=FEMAeff0607
Geom File=g01
Flow File=f01
Encroach Param=-1 ,0,0, 0

--- E141-00-00.p04 (plan) ---

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Plan Title=Storage Routing
Program Version=3.13
Short Identifier=Store_Rout
Geom File=g01
Flow File=f04
Unsteady Bridges Friction Slope Method= 1
Encroach Param=-1 ,0,0, 0
UNET Theta Warmup= 1
UNET DSS MLevel= 4
UNET DZMax Abort= 100
UNET Froude Reduction=False
UNET Froude Limit= 1
UNET Froude Power= 10
Echo Input=False
Echo Output=False
Detailed Automatic Start=False, 10

--- E141-00-00.f02 (steady flow) ---

Flow Title=Floodway
Version=Version 3.0.1  Mar 2001
Number of Profiles= 2
Profile Names=1PCT_100yr, 1PCTFloodway_100yrFW
River Rch & RM=E141-00-00,E141-00-00_0003       ,15147.0
    1459    1459
River Rch & RM=E141-00-00,E141-00-00_0003       ,13589.6
    1510    1510
River Rch & RM=E141-00-00,E141-00-00_0003       ,12594.7
    1570    1570
River Rch & RM=E141-00-00,E141-00-00_0003       ,11489.3
    1630    1630
River Rch & RM=E141-00-00,E141-00-00_0003       ,10422.8
    1680    1680
River Rch & RM=E141-00-00,E141-00-00_0003       ,9502.4
    1750    1750
River Rch & RM=E141-00-00,E141-00-00_0003       ,8336.2
    1840    1840
River Rch & RM=E141-00-00,E141-00-00_0003       ,6953.2
    1900    1900
River Rch & RM=E141-00-00,E141-00-00_0003       ,5929.3
    1980    1980
River Rch & RM=E141-00-00,E141-00-00_0003       ,4850.0
    2090    2090
River Rch & RM=E141-00-00,E141-00-00_0003       ,3225.6
    2210    2210
River Rch & RM=E141-00-00,E141-00-00_0003       ,1606.8
    2315    2315
Boundary for River Rch & Prof#=E141-00-00,E141-00-00_0003       , 1
Up Type= 0
Dn Type= 3
Dn Slope=.0018
Boundary for River Rch & Prof#=E141-00-00,E141-00-00_0003       , 2
Up Type= 0
Dn Type= 3
Dn Slope=.0018
DSS Import GetInterval= 0
DSS Import GetPeak= 0
DSS Import FillOption= 0

--- E141-00-00.f01 (steady flow) ---

Flow Title=FEMA Effective June 2007
Version=Version 3.0.1  Mar 2001
Number of Profiles= 4
Profile Names=10PCT_10yr, 2PCT_50yr, 1PCT_100yr, 0.2PCT_500yr
River Rch & RM=E141-00-00,E141-00-00_0003       ,15147.0
     836    1250    1459    2062
River Rch & RM=E141-00-00,E141-00-00_0003       ,13589.6
     860    1290    1510    2140
River Rch & RM=E141-00-00,E141-00-00_0003       ,12594.7
     890    1340    1570    2220
River Rch & RM=E141-00-00,E141-00-00_0003       ,11489.3
     920    1390    1630    2310
River Rch & RM=E141-00-00,E141-00-00_0003       ,10422.8
     940    1430    1680    2380
River Rch & RM=E141-00-00,E141-00-00_0003       ,9502.4
     980    1490    1750    2480
River Rch & RM=E141-00-00,E141-00-00_0003       ,8336.2
    1020    1560    1840    2610
River Rch & RM=E141-00-00,E141-00-00_0003       ,6953.2
    1050    1620    1900    2710
River Rch & RM=E141-00-00,E141-00-00_0003       ,5929.3
    1090    1680    1980    2810
River Rch & RM=E141-00-00,E141-00-00_0003       ,4850.0
    1140    1770    2090    2980
River Rch & RM=E141-00-00,E141-00-00_0003       ,3225.6
    1200    1870    2210    3160
River Rch & RM=E141-00-00,E141-00-00_0003       ,1606.8
    1244    1955    2315    3306
Boundary for River Rch & Prof#=E141-00-00,E141-00-00_0003       , 1
Up Type= 0
Dn Type= 3
Dn Slope=.0018
Boundary for River Rch & Prof#=E141-00-00,E141-00-00_0003       , 2
Up Type= 0
Dn Type= 3
Dn Slope=.0018
Boundary for River Rch & Prof#=E141-00-00,E141-00-00_0003       , 3
Up Type= 0
Dn Type= 3
Dn Slope=.0018
Boundary for River Rch & Prof#=E141-00-00,E141-00-00_0003       , 4
Up Type= 0
Dn Type= 3
Dn Slope=.0018
DSS Import GetInterval= 0
DSS Import GetPeak= 0
DSS Import FillOption= 0

--- E141-00-00.f04 (steady flow) ---

Flow Title= Storage Routing
Version=Version 3.0.1  Mar 2001
Number of Profiles= 7
Profile Names=0.25x10% flood,0.50x10% flood,10% flood,2% flood,1% flood,0.2% flood,1.25x0.2% flood
River Rch & RM=E141-00-00,E141-00-00_0003       ,15147.0
     120     240     484     676     773    1000    1250
River Rch & RM=E141-00-00,E141-00-00_0003       ,14753.6
     140     270     540     730     840    1100    1380
River Rch & RM=E141-00-00,E141-00-00_0003       ,11489.3
     150     290     580     800     920    1200    1500
River Rch & RM=E141-00-00,E141-00-00_0003       ,9502.4
     160     310     620     870    1000    1300    1630
River Rch & RM=E141-00-00,E141-00-00_0003       ,7968.8
     170     340     680     950    1100    1420    1780
River Rch & RM=E141-00-00,E141-00-00_0003       ,4981.4
     180     360     710     990    1150    1500    1880
River Rch & RM=E141-00-00,E141-00-00_0003       ,4061.8
     190     380     750    1070    1220    1600    2000
River Rch & RM=E141-00-00,E141-00-00_0003       ,1792.4
     200     400     800    1150    1310    1700    2130
Boundary for River Rch & Prof#=E141-00-00,E141-00-00_0003       , 1
Up Type= 0
Dn Type= 3
Dn Slope=.0018
Boundary for River Rch & Prof#=E141-00-00,E141-00-00_0003       , 2
Up Type= 0
Dn Type= 3
Dn Slope=.0018
Boundary for River Rch & Prof#=E141-00-00,E141-00-00_0003       , 3
Up Type= 0
Dn Type= 3
Dn Slope=.0018
Boundary for River Rch & Prof#=E141-00-00,E141-00-00_0003       , 4
Up Type= 0
Dn Type= 3
Dn Slope=.0018
Boundary for River Rch & Prof#=E141-00-00,E141-00-00_0003       , 5
Up Type= 0
Dn Type= 3
Dn Slope=.0018
Boundary for River Rch & Prof#=E141-00-00,E141-00-00_0003       , 6
Up Type= 0
Dn Type= 3
Dn Slope=.0018
Boundary for River Rch & Prof#=E141-00-00,E141-00-00_0003       , 7
Up Type= 0
Dn Type= 3
Dn Slope=.0018
DSS Import GetInterval= 0
DSS Import GetPeak= 0
DSS Import FillOption= 0

--- E141-00-00.g01 (geometry) ---

Geom Title=E141-00-00 June 2007
Version=Version 3.0.1  Mar 2001

River Reach=E141-00-00      ,E141-00-00_0003
Reach XY= 30
      3060795.82     13898297.06      3060830.14     13897370.74
      3060852.71     13897310.84      3060877.02     13897298.69
      3061018.51     13897277.86      3061058.44     13897191.05
      3061223.37     13892663.27      3061252.25       13892595.
       3061588.5       13892256.      3061601.84     13892224.04
      3061615.73     13891895.91      3061778.06     13891433.24
      3061807.75       13891386.      3063100.98     13890316.92
      3063152.19     13890252.68      3063194.73     13889000.95
      3063156.53     13888921.09      3063060.18     13888855.11
      3063022.85     13888796.09      3063035.87     13888389.84
      3063062.78     13888161.54      3063109.66     13888000.95
      3063364.86     13887397.65      3063804.97     13886732.72
       3063914.5       13886491.       3063998.5       13886129.
      3064000.28     13885747.48      3064060.25       13884830.
      3064134.83     13884668.48      3064311.04     13884529.59

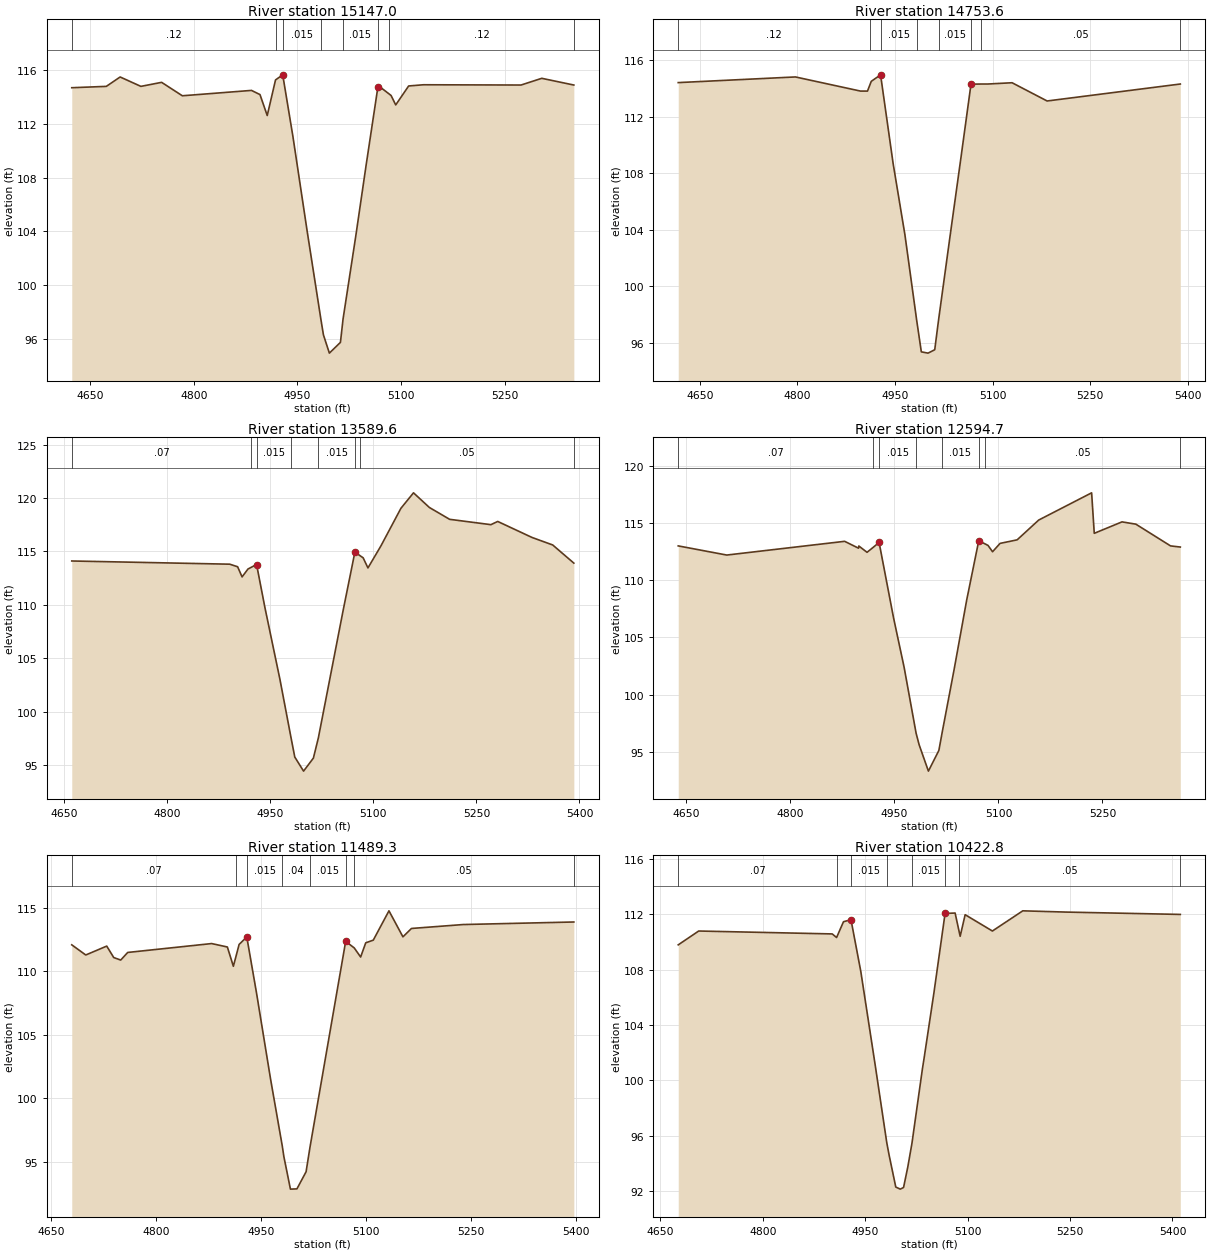
Type RM Length L Ch R = 1 ,15147.0 ,396.33,393.4,391.86
BEGIN DESCRIPTION:
Cross Section xs13
END DESCRIPTION:
XS GIS Cut Line= 2
      3061172.11     13898288.48      3060445.77     13898279.54
#Sta/Elev= 30
  4623.6   114.7  4673.6   114.8  4693.6   115.5  4723.6   114.8  4753.6   115.1
  4783.6   114.1  4883.6   114.5  4895.9  114.19  4906.4  112.63  4918.4  115.28
  4928.8  115.66  4943.5  111.09  4964.7  103.84    4984   97.47  4987.7    96.3
  4996.3   94.94  5012.3   95.74  5016.1   97.48  5034.4  103.62  5049.4  108.91
  5066.5  114.75  5066.7  114.87  5082.9  114.23  5085.6  114.12  5092.3  113.42
    5111  114.83  5132.4  114.92  5273.6   114.9  5303.6   115.4    5350   114.9
#Mann= 8 ,-1 , 0
  4623.6     .12       0  4918.4     .04       0  4928.8    .015       0
    4984     .04       0  5016.1    .015       0  5066.5     .04       0
  5082.9     .12       0    5350      .2       0
Bank Sta=4928.8,5066.5
XS Rating Curve= 0
Exp/Cntr=.3,.1

Type RM Length L Ch R = 1 ,14753.6 ,1141,1164,1149.12
BEGIN DESCRIPTION:
Cross Section xs12
Located At: 6030FT US WEST RD
END DESCRIPTION:
XS GIS Cut Line= 2
      3061189.99     13897881.73      3060418.96     13897899.61
#Sta/Elev= 22
    4617   114.4    4797   114.8    4897   113.8  4907.7   113.8    4912  114.31
  4913.5  114.49  4927.8  114.95  4947.1  108.67  4965.2  103.64  4983.3   97.58
  4990.4   95.36  5000.7   95.27    5011   95.51  5016.8   97.59    5035   103.7
  5051.4  109.14  5066.7  114.29  5082.1   114.3  5092.5   114.3  5129.8  114.39
  5183.6   113.1  5388.2   114.3
#Mann= 8 ,-1 , 0
    4617     .12       0    4912     .04       0  4927.8    .015       0
  4983.3     .04       0  5016.8    .015       0  5066.7     .04       0
  5082.1     .05       0  5388.2      .2       0
Bank Sta=4927.8,5066.7
XS Rating Curve= 0
Exp/Cntr=.3,.1

Type RM Length L Ch R = 1 ,13589.6 ,994.45,994.9,995.48
BEGIN DESCRIPTION:
Cross Section xs11
Located At: 4990FT US WEST RD
END DESCRIPTION:
XS GIS Cut Line= 2
      3061411.24      13896880.5      3060680.44     13896887.21
#Sta/Elev= 29
    4661   114.1    4891   113.8  4902.4  113.56  4908.9  112.61  4917.5  113.35
  4922.6  113.52    4930  113.77  4942.3  109.69    4964  103.02  4980.2   97.54
  4985.6   95.75  4998.4   94.43  5012.7   95.65  5019.9   97.53  5056.1  109.51
  5073.1  114.93  5080.3  114.61  5085.1   114.4  5092.1  113.45  5110.9   115.5
  5140.1  119.03  5158.4  120.48  5181.5  119.11    5211     118    5271   117.5
    5281   117.8    5331   116.3    5361   115.6  5391.8   113.9
#Mann= 8 ,-1 , 0
    4661     .07       0  4922.6     .04       0    4930    .015       0
  4980.2     .04       0  5019.9    .015       0  5073.1     .04       0
  5080.3     .05       0  5391.8      .2       0
Bank Sta=4930,5073.1
XS Rating Curve= 0
Exp/Cntr=.3,.1

Type RM Length L Ch R = 1 ,12594.7 ,1103.03,1105.4,1108.53
BEGIN DESCRIPTION:
Cross Section xs10
Located At: 4000FT US WEST RD
END DESCRIPTION:
XS GIS Cut Line= 2
      3061469.35     13895890.45      3060745.25     13895888.22
#Sta/Elev= 30
  4638.2     113  4708.2   112.2  4878.2   113.4  4898.2   112.8  4898.7  112.99
  4910.5  112.44  4919.5  112.88  4927.9   113.3  4948.7  106.72    4964  102.38
  4981.2   96.64  4985.6   95.62    4999   93.31  5014.1   95.12  5018.9   96.71
  5036.1   102.2  5054.2  108.26  5071.6  113.45  5081.2  113.16    5085  113.04
  5091.5  112.49  5102.4  113.22    5127  113.53  5158.1  115.26  5234.4  117.64
  5238.2   114.1  5278.2   115.1  5298.2   114.9  5348.2     113  5362.3   112.9
#Mann= 8 ,-1 , 0
  4638.2     .07       0  4919.5     .04       0  4927.9    .015       0
  4981.2     .04       0  5018.9    .015       0  5071.6     .04       0
  5081.2     .05       0  5362.3      .2       0
Bank Sta=4927.9,5071.6
XS Rating Curve= 0
Exp/Cntr=.3,.1

Type RM Length L Ch R = 1 ,11489.3 ,1070.12,1066.5,1062.75
BEGIN DESCRIPTION:
Cross Section xs09
Located At: 3RD US WEST RD
END DESCRIPTION:
XS GIS Cut Line= 2
      3061467.11     13894797.59      3060749.72     13894768.54
#Sta/Elev= 30
  4679.2   112.1  4699.2   111.3  4729.2     112  4739.2   111.1  4749.2   110.9
  4759.2   111.5  4879.2   112.2  4901.7  111.93  4910.3  110.41  4913.8  111.14
  4918.5  112.13  4929.5  112.72  4943.4  108.31  4963.5  101.52  4980.3   96.23
  4982.5   95.42  4991.9   92.85  5001.2   92.87  5014.3   94.22  5019.8   96.13
  5070.9  112.37  5083.1  111.86  5092.3  111.14  5099.6  112.26  5110.4  112.47
  5132.8  114.78  5152.8  112.73    5165  113.39  5239.2   113.7  5397.2   113.9
#Mann= 8 ,-1 , 0
  4679.2     .07       0  4913.8     .04       0  4929.5    .015       0
  4980.3     .04       0  5019.8    .015       0  5070.9     .04       0
  5083.1     .05       0  5397.2      .2       0
Bank Sta=4929.5,5070.9
XS Rating Curve= 0
Exp/Cntr=.3,.1

Type RM Length L Ch R = 1 ,10422.8 ,919.4,920.4,921.08
BEGIN DESCRIPTION:
Cross Section xs08
Located At: 2ND US WEST RD
END DESCRIPTION:
XS GIS Cut Line= 2
      3061509.58     13893715.91       3060774.3     13893722.62
#Sta/Elev= 28
  4676.2   109.8  4706.2   110.8  4901.7  110.59  4908.1  110.33    4909  110.43
  4918.2  111.47  4929.2  111.62  4943.6  107.87  4964.8  101.06  4981.6    95.5
  4985.2   94.56  4994.8   92.29  5001.4   92.14  5006.2   92.26  5012.4   93.74
  5018.5   95.46  5033.8  100.83  5036.1  101.55  5050.6  106.31    5067  112.07
  5081.7   112.1  5086.7  110.96  5089.1  110.42  5096.4  111.98  5136.3   110.8
  5180.8  112.26  5243.4  112.17  5411.5     112
#Mann= 8 ,-1 , 0
  4676.2     .07       0    4909     .04       0  4929.2    .015       0
  4981.6     .04       0  5018.5    .015       0    5067     .04       0
  5086.7     .05       0  5411.5      .2       0
Bank Sta=4929.2,5067
XS Rating Curve= 0
Exp/Cntr=.3,.1

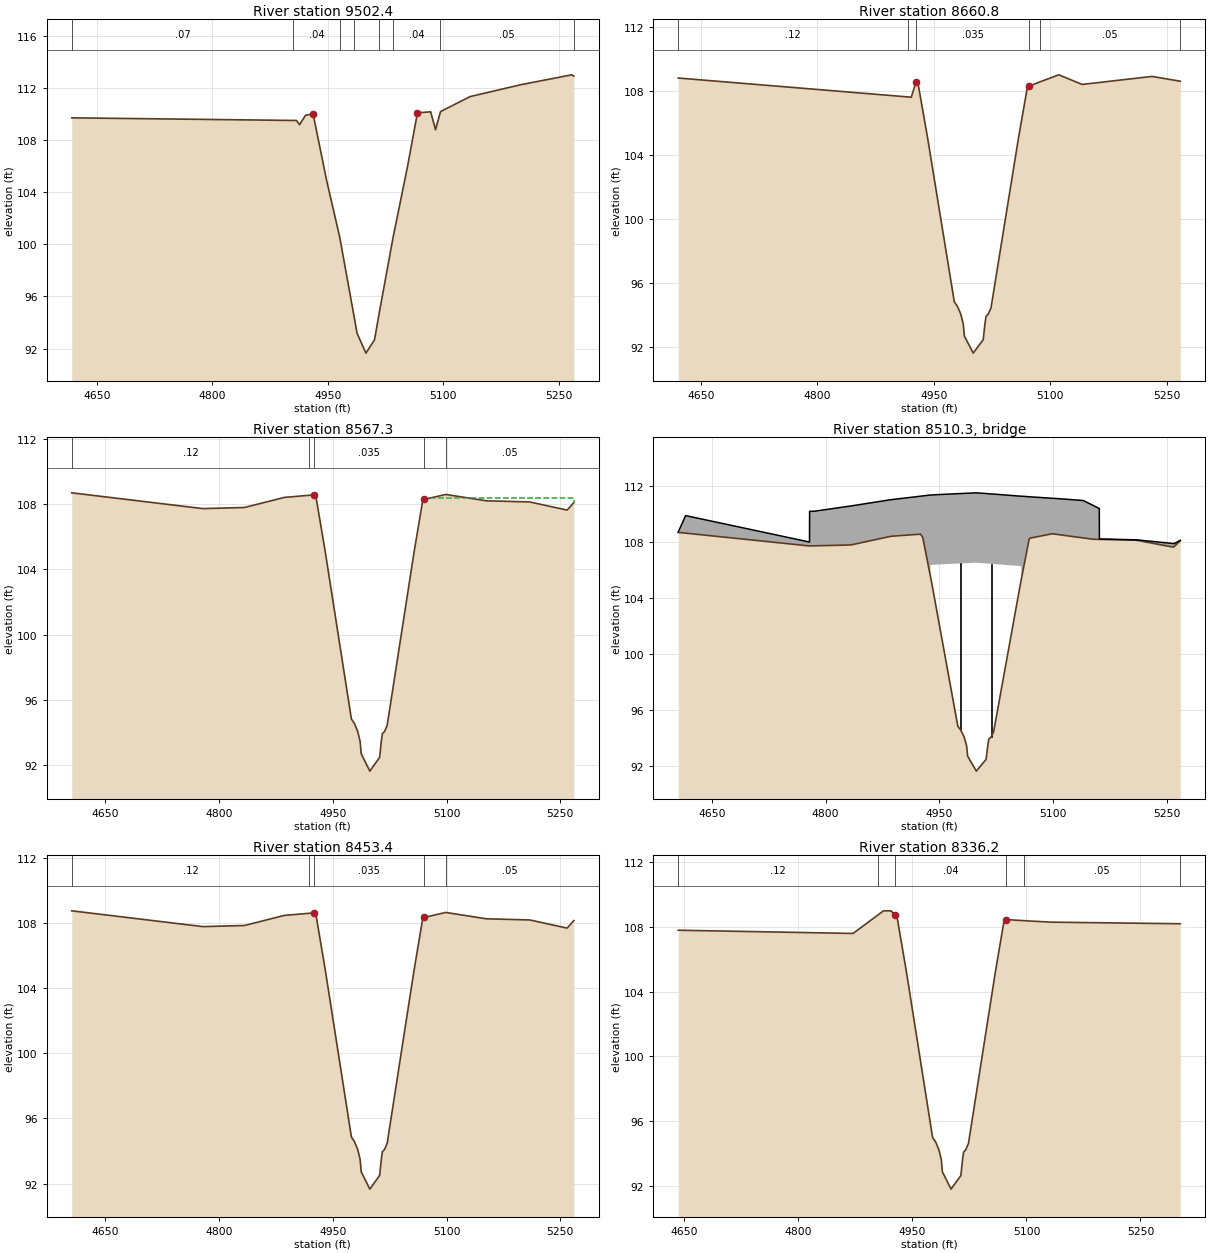
Type RM Length L Ch R = 1 ,9502.4  ,842.61,841.6,831.98
BEGIN DESCRIPTION:
Cross Section xs07
Located At: US WEST RD
END DESCRIPTION:
XS GIS Cut Line= 2
      3061603.44     13892799.61      3060950.71     13892799.24
#Sta/Elev= 24
  4617.1   109.7  4905.1   109.5  4909.3   109.5  4913.2  109.17  4920.9  109.89
  4930.8  110.01  4948.3  104.93  4965.5  100.53  4983.5   94.66    4988   93.17
  4999.5   91.65  5010.7   92.67  5016.4    94.6  5034.7  100.49  5053.7     106
  5066.5  110.09  5083.7  110.16    5090  108.79  5096.3  110.14  5096.5  110.18
  5134.9  111.33  5201.5  112.25  5267.1     113  5269.8   112.9
#Mann= 8 ,-1 , 0
  4617.1     .07       0  4905.1     .04       0  4965.5    .015       0
  4983.5     .04       0  5016.4    .015       0  5034.7     .04       0
  5096.3     .05       0  5269.8      .2       0
Bank Sta=4930.8,5066.5
XS Rating Curve= 0
Exp/Cntr=.3,.1

Type RM Length L Ch R = 1 ,8660.8  ,93,93.55,94
BEGIN DESCRIPTION:
West - 4
Formerly Cross Section xs06.7
END DESCRIPTION:
XS GIS Cut Line= 2
      3061981.14     13892122.44      3061335.26     13892095.63
#Sta/Elev= 26
    4621   108.8  4916.6  107.62    4921   107.6 4927.25  108.57 4930.15  108.34
 4941.95  105.09 4976.45   94.82 4980.35   94.55 4984.75   94.06 4987.95   93.44
 4989.35   92.69 5000.75   91.62 5013.65   92.46 5015.95   93.47 5017.25   93.91
 5020.25   94.06 5020.55   94.11 5023.65   94.44 5058.95  105.02 5070.55  108.24
 5072.75   108.3  5086.7  108.56    5111     109    5141   108.4    5231   108.9
  5267.4   108.6
#Mann= 6 ,-1 , 0
    4621     .12       0  4916.6     .04       0 4927.25    .035       0
 5072.75     .04       0  5086.7     .05       0  5267.4      .2       0
Bank Sta=4927.25,5072.75
XS Rating Curve= 0
Exp/Cntr=.5,.3

Type RM Length L Ch R = 1 ,8567.3  ,113.5,113.9,114
BEGIN DESCRIPTION:
West - 3
Formerly E141-00-00-04
END DESCRIPTION:
XS GIS Cut Line= 2
      3061999.99     13892024.88      3061338.46     13892000.13
#Sta/Elev= 27
  4605.8   108.7  4778.8  107.73  4833.5   107.8  4886.2  108.42  4919.2  108.55
  4925.3  108.57  4928.2  108.34    4940  105.09  4974.5   94.82  4978.4   94.55
  4982.8   94.06    4986   93.44  4987.4   92.69  4998.8   91.62  5011.7   92.46
    5014   93.47  5015.3   93.91  5018.3   94.06  5021.7   94.44    5057  105.02
  5068.6  108.24  5070.8   108.3  5098.9   108.6  5152.5  108.21  5209.7  108.14
  5258.9  107.64  5267.8   108.1
#Mann= 5 ,-1 , 0
  4605.8     .12       0  4919.2     .04       0  4925.3    .035       0
  5070.8     .04       0  5098.9     .05       0
#XS Ineff= 2 , 0
       0    4925   108.4    5070       0   108.4
Permanent Ineff=
       F       F
Bank Sta=4925.3,5070.8
XS Rating Curve= 0
Exp/Cntr=.5,.3

Type RM Length L Ch R = 3 ,8510.3  ,,,
BEGIN DESCRIPTION:
WEST ROAD
Structure ID: E141-00-00-04
END DESCRIPTION:
Bridge Culvert--1,0,-1,-1, 0
Deck Dist Width WeirC Skew NumUp NumDn MinLoCord MaxHiCord MaxSubmerge Is_Ogee
10,93.9,2.6,0, 51, 51, , , .95, 0, ,,,
  4605.8  4615.6  4735.7  4778.8 4778.89    4779 4779.11  4784.8  4829.7  4833.5
  4886.2  4886.4  4919.2  4925.3  4928.2  4938.1 4938.21  4938.3    4940  4974.5
  4978.4  4982.8    4986  4987.4  4998.3  4998.8  5011.7    5014  5015.3  5018.3
  5018.6  5021.7    5057 5058.09  5058.2  5058.3  5068.6  5070.8  5098.9    5099
  5110.6  5139.7  5152.5 5160.89    5161 5161.11  5209.1  5209.7  5258.9  5259.6
  5267.8
  108.73   109.9  108.51  108.01  108.01  110.21  110.21  110.21  110.56  110.59
  111.04  111.04  111.25  111.29  111.31  111.37  111.37  111.37  111.38  111.47
  111.48  111.49   111.5   111.5  111.53  111.53  111.48  111.47  111.46  111.45
  111.45  111.44  111.29  111.29  111.29  111.29  111.25  111.24  111.14  111.14
   111.1  110.98  110.64  110.41  110.41  108.23  108.17  108.17   107.9   107.9
  108.13
   108.7  108.65     108  107.73  107.73  107.73  107.73  107.74   107.8   107.8
  108.42  108.42  108.55  108.57  108.34  105.61  105.58  106.37  106.38  106.47
  106.48  106.49   106.5   106.5  106.53  106.53  106.48  106.47  106.46  106.45
  106.45  106.44  106.29  106.29  105.35  105.38  108.24   108.3   108.6   108.6
  108.52   108.3  108.21   108.2   108.2   108.2  108.14  108.14  107.64  107.68
   108.1
  4605.8  4615.6  4735.7  4778.8 4778.89    4779 4779.11  4784.8  4829.7  4833.5
  4886.2  4886.4  4919.2  4925.3  4928.2  4938.1 4938.21  4938.3    4940  4974.5
  4978.4  4982.8    4986  4987.4  4998.3  4998.8  5011.7    5014  5015.3  5018.3
  5018.6  5021.7    5057 5058.09  5058.2  5058.3  5068.6  5070.8  5098.9    5099
  5110.6  5139.7  5152.5 5160.89    5161 5161.11  5209.1  5209.7  5258.9  5259.6
  5267.8
  108.73   109.9  108.51  108.01  108.01  110.21  110.21  110.21  110.56  110.59
  111.04  111.04  111.25  111.29  111.31  111.37  111.37  111.37  111.38  111.47
  111.48  111.49   111.5   111.5  111.53  111.53  111.48  111.47  111.46  111.45
  111.45  111.44  111.29  111.29  111.29  111.29  111.25  111.24  111.14  111.14
   111.1  110.98  110.64  110.41  110.41  108.23  108.17  108.17   107.9   107.9
  108.13
  108.73  108.68  108.03  107.76  107.76  107.76  107.76  107.77  107.83  107.83
  108.45  108.45  108.58   108.6  108.37  105.64  105.61   106.4  106.41   106.5
  106.51  106.52  106.53  106.53  106.56  106.56  106.51   106.5  106.49  106.48
  106.48  106.47  106.32  106.32  105.38  105.41  108.27  108.33  108.63  108.63
  108.55  108.33  108.24  108.23  108.23  108.23  108.17  108.17  107.67  107.71
  108.13
Pier Skew, UpSta & Num, DnSta & Num=  ,4978, 2 ,4978, 2 , 0 , 0 , 0 ,,
     1.4     1.4
   93.52  107.48
     1.4     1.4
   93.55  107.51
Pier Skew, UpSta & Num, DnSta & Num=  ,5018.3, 2 ,5018.3, 2 , 0 , 0 , 0 ,,
     1.4     1.4
   93.02  107.45
     1.4     1.4
   93.06  107.48
BR Coef= 1 , 1 , 0 ,1.25, 0 ,,,.8,0,2,0,
WSPro=,,,, 1 ,,,, 0 ,,,, 0 ,,,,-1 ,-1 ,-1 , 0 , 0 , 0 , 0 , 0
BC Design=,, 0 ,, 0 ,,,,,,

Type RM Length L Ch R = 1 ,8453.4  ,117,117.15,117.5
BEGIN DESCRIPTION:
West - 2
Formerly E141-00-00-04
END DESCRIPTION:
XS GIS Cut Line= 2
      3062009.48     13891910.08      3061347.96     13891885.33
#Sta/Elev= 27
  4605.8  108.74  4778.8  107.77  4833.5  107.84  4886.2  108.46  4919.2  108.59
  4925.3  108.61  4928.2  108.38    4940  105.13  4974.5   94.86  4978.4   94.59
  4982.8    94.1    4986   93.48  4987.4   92.73  4998.8   91.66  5011.7    92.5
    5014   93.51  5015.3   93.95  5018.3    94.1  5021.7   94.48    5057  105.06
  5068.6  108.28  5070.8  108.34  5098.9  108.64  5152.5  108.25  5209.7  108.18
  5258.9  107.68  5267.8  108.14
#Mann= 5 ,-1 , 0
  4605.8     .12       0  4919.2     .04       0  4925.3    .035       0
  5070.8     .04       0  5098.9     .05       0
#XS Ineff= 2 , 0
       0    4925     108    5070       0     108
Permanent Ineff=
       F       F
Bank Sta=4925.3,5070.8
XS Rating Curve= 0
Exp/Cntr=.5,.3

Type RM Length L Ch R = 1 ,8336.2  ,340.74,367.4,396.68
BEGIN DESCRIPTION:
West - 1
Formerly Cross Section xs06.5
END DESCRIPTION:
XS GIS Cut Line= 2
       3062010.3     13891801.47      3061350.14     13891778.41
#Sta/Elev= 26
  4641.8   107.8  4871.8   107.6  4904.5  108.74  4911.8     109  4921.8     109
 4927.25  108.73 4930.15   108.5 4941.95  105.25 4976.45   94.98 4980.35   94.71
 4984.75   94.22 4987.95    93.6 4989.35   92.85 5000.75   91.78 5013.65   92.62
 5015.95   93.63 5017.25   94.07 5020.25   94.22 5020.55   94.27 5023.65    94.6
 5058.95  105.18 5070.55   108.4 5072.75  108.46    5097  108.39  5131.8   108.3
  5302.4   108.2
#Mann= 6 ,-1 , 0
  4641.8     .12       0  4904.5     .04       0 4927.25     .04       0
 5072.75     .04       0    5097     .05       0  5302.4      .2       0
Bank Sta=4927.25,5072.75
XS Rating Curve= 0
Exp/Cntr=.3,.1

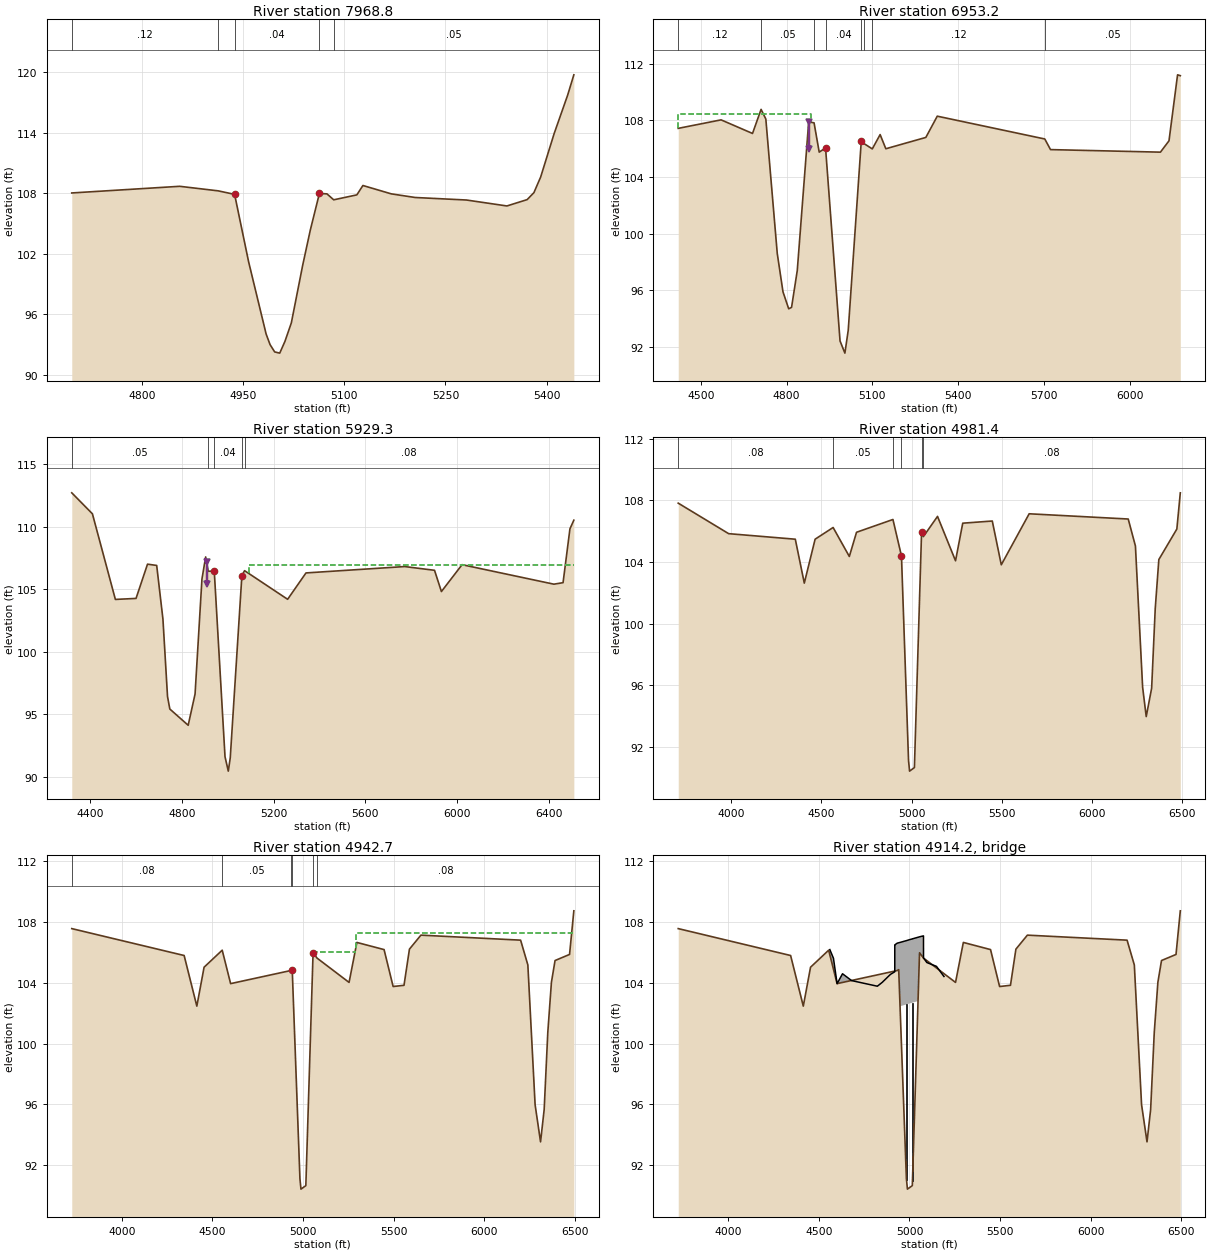
Type RM Length L Ch R = 1 ,7968.8  ,986.77,1015.6,1049.66
BEGIN DESCRIPTION:
Cross Section xs06
Located At: DS WEST RD
END DESCRIPTION:
XS GIS Cut Line= 3
      3062050.11     13891570.94      3061619.45     13891370.36
      3061374.91     13891257.85
#Sta/Elev= 28
  4696.1  108.04  4856.1   108.7  4913.1  108.25  4937.5   107.9  4958.3   101.2
  4984.2   94.05  4990.1   92.99  4996.9   92.27  5004.4   92.15  5012.1   93.31
  5021.6   95.15  5038.4  100.86  5049.7  104.35  5063.2  107.99  5074.4  107.95
  5084.4  107.36  5118.7  107.85  5127.7  108.78  5169.8  107.95  5205.2  107.59
  5281.2  107.34  5341.2  106.75  5371.2  107.38  5381.2  108.07  5391.2  109.62
  5411.2  113.93  5431.2  117.74  5440.4  119.76
#Mann= 5 ,-1 , 0
  4696.1     .12       0  4913.1     .04       0  4937.5     .04       0
  5063.2     .04       0  5084.4     .05       0
Bank Sta=4937.5,5063.2
XS Rating Curve= 0
Exp/Cntr=.3,.1

Type RM Length L Ch R = 1 ,6953.2  ,1020.9,1023.9,968.65
BEGIN DESCRIPTION:
Cross Section xs05 **See Note**
Located At: 2ND DS WEST RD
**Note**
The levee prevents flows from filling the detention pond.  This levee is not intended to represent a certified levee, but a method to accurately model flows not entering the detention pond.
END DESCRIPTION:
XS GIS Cut Line= 5
      3062919.52     13891199.73      3062691.96     13890954.29
      3062420.16     13890644.44      3061902.35     13890068.17
      3061676.35     13890027.89
#Sta/Elev= 30
  4420.6  107.44  4570.6  108.04  4680.6  107.08  4710.6  108.78  4727.2   108.1
  4767.2    98.6  4787.2    95.9  4807.2    94.7  4817.2    94.8  4837.2    97.4
  4877.2   107.9    4896  107.83    4914  105.76  4936.2  106.06  4986.9   92.43
  5003.9   91.57  5015.6   93.19  5061.2  106.53  5071.9  106.35  5099.8  105.99
  5127.2     107  5147.2     106  5287.2   106.8  5327.2   108.3  5703.5  106.69
  5723.5  105.94  6108.2  105.76  6138.2  106.56  6168.2  111.22  6177.8  111.16
#Mann= 8 ,-1 , 0
  4420.6     .12       0  4710.6     .05       0    4896     .04       0
  4936.2     .04       0  5061.2     .04       0  5071.9     .05       0
  5099.8     .12       0  5703.5     .05       0
Levee=-1,4880,106,0,,,,
#XS Ineff= 2 , 0
       0  4884.4  108.45               0
Permanent Ineff=
       F       F
Bank Sta=4936.2,5061.2
XS Rating Curve= 0
Exp/Cntr=.3,.1

Type RM Length L Ch R = 1 ,5929.3  ,962.57,947.9,941.97
BEGIN DESCRIPTION:
Cross Section xs04 **See Note**
**Note**
The levee prevents flows from filling the detention pond.  This levee is not intended to represent a certified levee, but a method to accurately model flows not entering the detention pond.
END DESCRIPTION:
XS GIS Cut Line= 4
      3063790.98     13890276.28      3063428.23     13890070.31
      3063000.94     13890022.95      3061671.87     13889848.88
#Sta/Elev= 30
  4320.6   112.7  4410.6  111.02  4510.6  104.17  4600.6  104.25  4650.6  106.99
  4690.6  106.89  4717.8   102.6  4737.8    96.4  4747.8    95.4  4827.8    94.1
  4857.8    96.6  4887.8   105.8  4903.9  107.57  4915.2  106.42  4941.4  106.45
  4988.3   91.58  5002.6   90.43  5011.1   91.49  5061.8  106.08  5073.5  106.47
  5261.1  104.18  5341.1  106.29  5771.1   106.8  5901.1   106.5  5931.1   104.8
  6021.1  106.95  6421.1  105.39  6461.1  105.51  6491.1  109.82  6508.1  110.51
#Mann= 5 ,-1 , 0
  4320.6     .05       0  4915.2     .04       0  4941.4     .04       0
  5061.8     .04       0  5073.5     .08       0
Levee=-1,4908,105.4,0,,,,
#XS Ineff= 2 , 0
       0  4903.9  107.57    5091       0  106.89
Permanent Ineff=
       F       F
Bank Sta=4941.4,5061.8
XS Rating Curve= 0
Exp/Cntr=.3,.1

Type RM Length L Ch R = 1 ,4981.4  ,39,38.75,38.5
BEGIN DESCRIPTION:
Windfern Forest - 4
Formerly Cross Section xs03.7
END DESCRIPTION:
XS GIS Cut Line= 5
      3064482.43     13889204.42       3063380.9     13889097.98
      3063047.74     13889091.04      3062551.29     13889202.18
      3061712.15     13889195.47
#Sta/Elev= 30
  3704.6  107.81  3984.6  105.83  4354.6  105.47  4404.6  102.62  4464.6  105.47
  4564.6  106.23  4654.6  104.35  4694.6  105.92  4896.8  106.75 4944.15  104.38
 4983.35   91.11 4989.15   90.42 5015.95   90.65 5055.85  105.97  5065.8  105.64
  5144.3  106.95  5244.3  104.07  5284.3  106.51  5448.4  106.65  5498.4  103.81
  5653.2  107.12  6203.2  106.78  6243.2  105.03  6283.2   95.86  6303.2   93.96
  6333.2    95.8  6353.2  100.97  6373.2  104.15  6473.2  106.13  6492.4  108.48
#Mann= 6 ,-1 , 0
  3704.6     .08       0  4564.6     .05       0  4896.8     .04       0
 4944.15    .035       0 5055.85     .04       0  5065.8     .08       0
#XS Ineff= 2 ,-1
    4354    4694     105 5138.21 6483.74  106.77
Permanent Ineff=
       F       F
Bank Sta=4944.15,5055.85
XS Rating Curve= 0
Exp/Cntr=.5,.3

Type RM Length L Ch R = 1 ,4942.7  ,56.5,56.9,57.4
BEGIN DESCRIPTION:
Windfern Forest - 3
Formerly E141-00-00-03
END DESCRIPTION:
XS GIS Cut Line= 5
      3064460.09     13889183.46      3063497.88     13889060.23
      3063108.55     13889045.25      3062553.57     13889163.32
      3061709.95     13889172.28
#Sta/Elev= 30
  3724.2  107.56  4344.2  105.79  4414.2  102.46  4454.2  105.02  4554.2  106.14
  4600.6  103.94  4931.9   104.8  4940.5  104.86    4983   91.11  4988.7   90.42
  5015.6   90.65  5055.5  105.97 5077.41  105.62  5254.1  104.02  5297.2  106.65
  5447.2  106.18  5497.2  103.75  5557.2  103.83  5587.2  106.21  5650.5  107.13
  6200.5   106.8  6240.5  105.17  6280.5   95.97  6310.5   93.53  6330.5   95.66
  6350.5  100.73  6370.5  104.03  6390.5  105.46  6470.5  105.86  6494.2  108.73
#Mann= 6 ,-1 , 0
  3724.2     .08       0  4554.2     .05       0  4931.9     .04       0
  4940.5    .035       0  5055.5     .04       0 5077.41     .08       0
#XS Ineff= 3 ,-1
 4235.77 4930.89  104.77 5060.98    5290     106    5291  6487.8  107.29
Permanent Ineff=
       F       F       F
Bank Sta=4940.5,5055.5
XS Rating Curve= 0
Exp/Cntr=.5,.3

Type RM Length L Ch R = 3 ,4914.2  ,,,
BEGIN DESCRIPTION:
WINDFERN FOREST DRIVE
Structure ID: E141-00-00-03
END DESCRIPTION:
Bridge Culvert--1,0,-1,-1, 0
Deck Dist Width WeirC Skew NumUp NumDn MinLoCord MaxHiCord MaxSubmerge Is_Ogee
10,36.9,2.6,0, 40, 40, , , .95, 0, 1,1,,
  4560.6  4580.6  4600.6  4630.6  4680.6  4818.8  4822.8  4847.1  4849.3  4895.1
  4896.1  4896.3 4918.79  4918.9 4919.01  4931.9  4940.5  4943.8 4950.31  4950.4
    4983  4983.5  4988.7    5002  5015.6  5016.4    5017 5046.69  5046.8  5055.5
    5065  5068.6 5077.19  5077.3 5077.41  5095.7  5097.4  5145.9  5148.6  5190.3
  106.18  105.61  103.94  104.59  104.14  103.78  103.77     104  104.02  104.55
  104.56  104.56  104.72  106.49  106.49   106.6  106.63  106.64  106.66  106.66
  106.77  106.77  106.79  106.84  106.88  106.88  106.89  106.99  106.99  107.02
  107.05  107.06  107.08  107.08  105.63  105.33  105.32  105.09  105.08  104.41
                                                                                
                                                                          102.46
  102.57  102.57  102.59  102.64  102.68  102.68  102.69  102.79
                                                                                
  4560.6  4580.6  4600.6  4630.6  4680.6  4818.8  4822.8  4847.1  4849.3  4895.1
  4896.1  4896.3 4918.79  4918.9 4919.01  4931.9  4940.5  4943.8 4950.31  4950.4
    4983  4983.5  4988.7    5002  5015.6  5016.4    5017 5046.69  5046.8  5055.5
    5065  5068.6 5077.19  5077.3 5077.41  5095.7  5097.4  5145.9  5148.6  5190.3
  106.18  105.61  103.94  104.59  104.14  103.78  103.77     104  104.02  104.55
  104.56  104.56  104.72  106.49  106.49   106.6  106.63  106.64  106.66  106.66
  106.77  106.77  106.79  106.84  106.88  106.88  106.89  106.99  106.99  107.02
  107.05  107.06  107.08  107.08  105.63  105.33  105.32  105.09  105.08  104.41
                                                                                
                                                                          102.46
  102.57  102.57  102.59  102.64  102.68  102.68  102.69  102.79
                                                                                
Pier Skew, UpSta & Num, DnSta & Num=  ,4983.5, 2 ,4983.5, 2 , 0 , 0 , 0 ,,
     1.3     1.3
   89.92  103.57
     1.3     1.3
   89.81  103.46
Pier Skew, UpSta & Num, DnSta & Num=  ,5016.4, 2 ,5016.4, 2 , 0 , 0 , 0 ,,
     1.3     1.3
   89.74  103.69
     1.3     1.3
   89.63  103.58
BR Coef= 1 , 1 , 0 ,1.25, 0 ,,,.8,0,2,0,
WSPro=,,,, 1 ,,,, 0 ,,,, 0 ,,,,-1 ,-1 ,-1 , 0 , 0 , 0 , 0 , 0
BC Design=,, 0 ,, 0 ,,,,,,