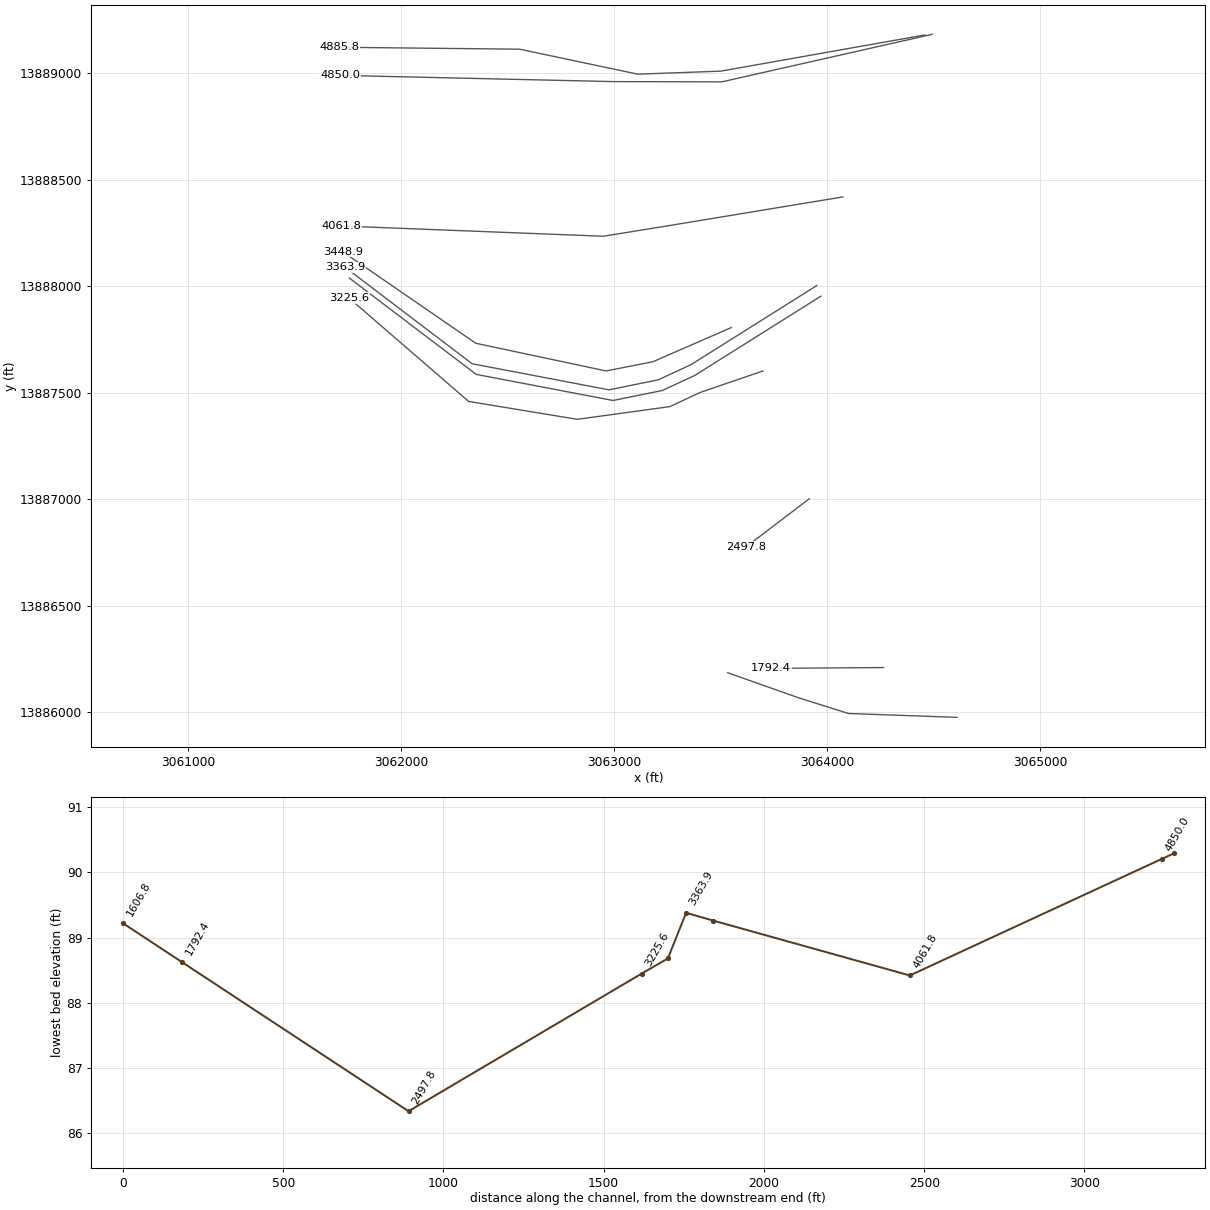
HEC-RAS study E141-00-00.prj: E141-00-00

--- E141-00-00.g01 (geometry) --- (continued)

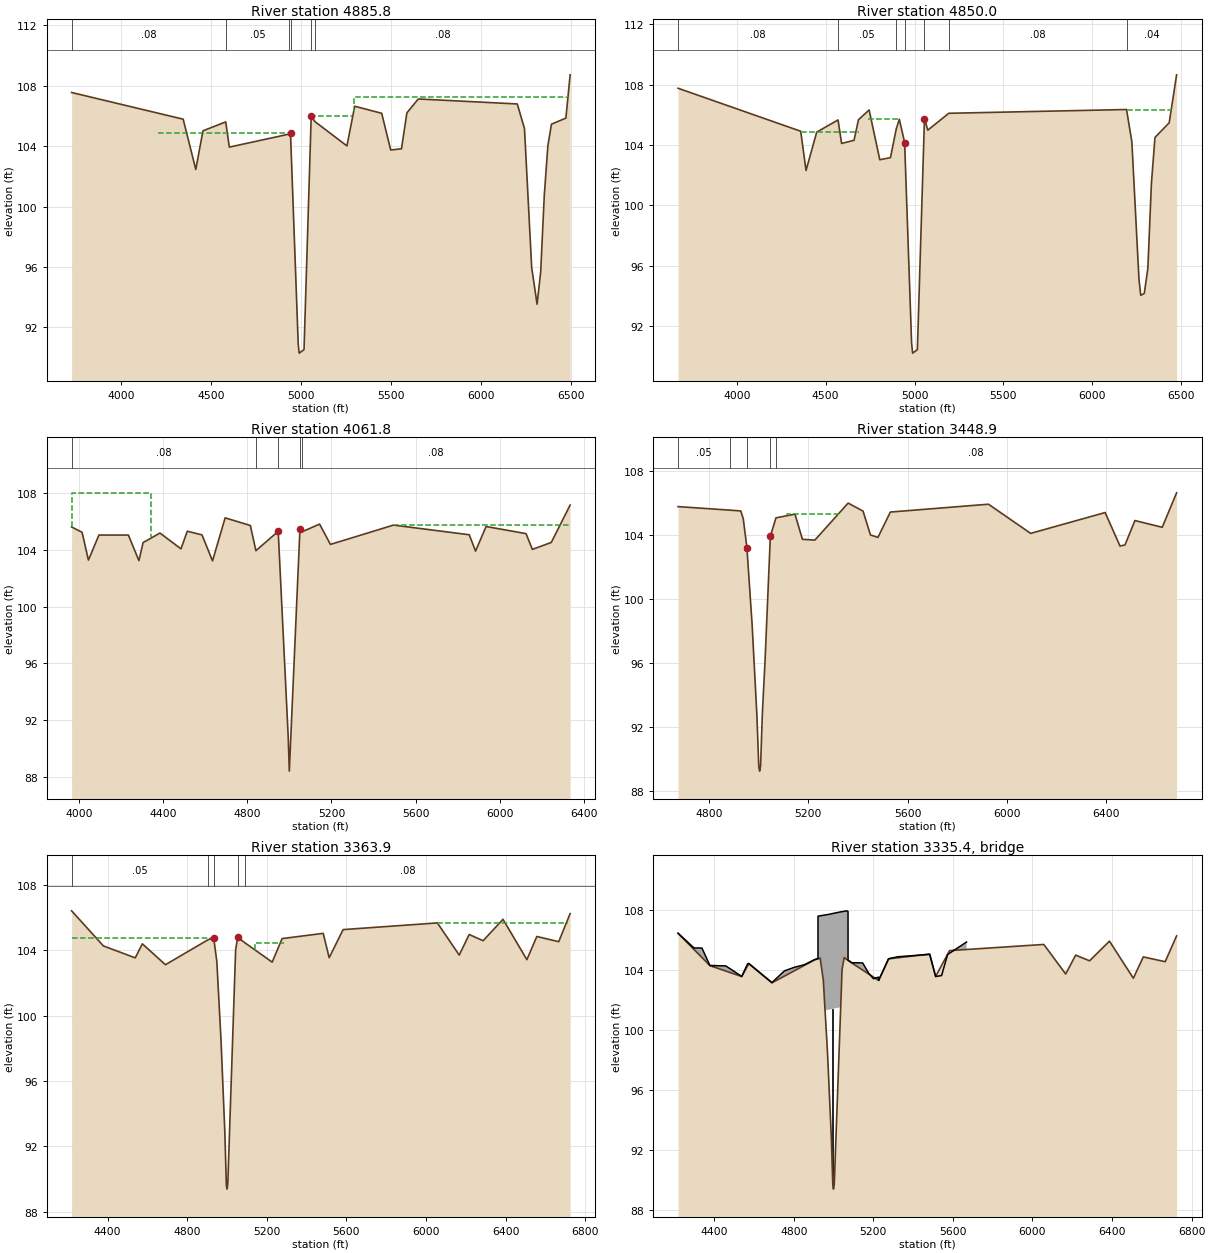
Type RM Length L Ch R = 1 ,4885.8  ,35.75,35.75,35.75
BEGIN DESCRIPTION:
Windfern Forest - 2
Formerly E141-00-00-03
END DESCRIPTION:
XS GIS Cut Line= 5
       3064457.5     13889179.13      3063499.63     13889009.36
      3063110.25     13888995.19      3062555.31     13889112.45
       3061711.7      13889121.4
#Sta/Elev= 30
  3724.2  107.56  4344.2  105.79  4414.2  102.46  4454.2  105.02  4580.6  105.61
  4600.6  103.94  4931.9   104.8  4940.5  104.86  4983.5   90.86  4988.7   90.29
  5015.6   90.52  5055.5  105.97 5077.41  105.62  5254.1  104.02  5297.2  106.65
  5447.2  106.18  5497.2  103.75  5557.2  103.83  5587.2  106.21  5650.5  107.13
  6200.5   106.8  6240.5  105.17  6280.5   95.97  6310.5   93.53  6330.5   95.66
  6350.5  100.73  6370.5  104.03  6390.5  105.46  6470.5  105.86  6494.2  108.73
#Mann= 6 ,-1 , 0
  3724.2     .08       0  4580.6     .05       0  4931.9     .04       0
  4940.5    .035       0  5055.5     .04       0 5077.41     .08       0
#XS Ineff= 3 ,-1
 4203.25 4930.89   104.9 5056.91    5290     106    5291 6483.74  107.23
Permanent Ineff=
       F       F       F
Bank Sta=4940.5,5055.5
XS Rating Curve= 0
Exp/Cntr=.5,.3

Type RM Length L Ch R = 1 ,4850.0  ,776.38,788.2,784.48
BEGIN DESCRIPTION:
Windfern Forest - 1   **See Note**
Formerly Cross Section xs03.5
END DESCRIPTION:
XS GIS Cut Line= 4
      3064491.38     13889182.04      3063504.57     13888959.09
      3062995.84     13888960.24      3061712.15      13888989.6
#Sta/Elev= 30
  3669.6  107.77  4359.6  104.92  4389.6  102.32  4449.6  104.86  4569.6  105.67
  4589.6  104.11  4659.6  104.32  4684.5  105.68  4744.5  106.33  4804.5  103.03
  4864.5  103.17  4897.2  105.08  4914.5  105.71 4944.15  104.17 4983.35    90.9
 4989.15   90.21 5015.95   90.44 5055.85  105.76  5074.5  104.99  5192.5  106.11
  6192.5  106.36  6222.5  104.22  6262.5   95.11  6272.5   94.04  6292.5   94.17
  6312.5   95.84  6332.5  101.46  6352.5  104.51  6432.5  105.48  6474.2  108.66
#Mann= 7 ,-1 , 0
  3669.6     .08       0  4569.6     .05       0  4897.2     .04       0
 4944.15    .035       0 5055.85     .04       0  5192.5     .08       0
  6192.5     .04       0
#XS Ineff= 3 ,-1
    4360    4685   104.9 4736.69 4914.24  105.71 6192.75    6450  106.36
Permanent Ineff=
       F       F       F
Bank Sta=4944.15,5055.85
XS Rating Curve= 0
Exp/Cntr=.3,.1

Type RM Length L Ch R = 1 ,4061.8  ,595.07,612.9,630.29
BEGIN DESCRIPTION:
Cross Section xs03 **See Note**
Located At: US MAUNA LOA
The ineffective in the left overbank models a spill out of E141-00-00 watershed and into E125-00-00
END DESCRIPTION:
XS GIS Cut Line= 4
      3064072.93     13888418.99      3063232.86     13888280.31
      3062947.54      13888234.4      3061718.86     13888282.49
#Sta/Elev= 30
  3964.8   105.6  4014.8  105.22  4044.8  103.27  4094.8  105.03  4234.8  105.03
  4284.8  103.23  4304.8   104.5  4384.8  105.17  4484.8  104.06  4514.8   105.3
  4584.8  105.04  4634.8  103.21  4694.8  106.24  4814.5   105.7    4841  103.93
    4947  105.29  4994.5   90.85  4999.8   88.42  5050.5  105.49  5060.4  105.26
  5143.8   105.8  5195.2  104.37  5495.2  105.73  5855.2  105.05  5885.2   103.9
  5935.2  105.63  6125.2  105.13  6155.2  104.02  6245.2  104.51  6334.8  107.14
#Mann= 5 ,-1 , 0
  3964.8     .08       0    4841     .04       0    4947     .04       0
  5050.5     .04       0  5060.4     .08       0
#XS Ineff= 2 , 0
       0    4340     108 5493.72       0  105.74
Permanent Ineff=
       F       F
Bank Sta=4947,5050.5
XS Rating Curve= 0
Exp/Cntr=.3,.1

Type RM Length L Ch R = 1 ,3448.9  ,75.29,85.05,77.84
BEGIN DESCRIPTION:
Mauna Loa - 4
Formerly Cross Section xs02.7
END DESCRIPTION:
XS GIS Cut Line= 5
      3063549.03     13887805.69       3063181.5     13887645.41
      3062961.51      13887602.1      3062349.89     13887732.01
      3061725.58     13888161.65
#Sta/Elev= 30
  4675.4  105.76  4883.6  105.54    4928  105.49    4938  105.01 4952.75   103.2
 4973.85   98.37 4992.95   92.75 5000.65    89.5 5004.05   89.26 5007.85   89.58
 5014.95   92.84 5025.95   96.19 5047.25  103.92  5069.9  105.06  5146.4  105.29
  5176.4  103.72  5226.4  103.67  5360.6  105.98  5420.6  105.48  5450.6  103.99
  5480.6  103.84  5530.6  105.42  5925.8  105.91  6095.8  104.09  6395.8  105.39
  6455.8   103.3  6475.8  103.37  6515.8  104.89  6625.8  104.47  6683.7  106.62
#Mann= 5 ,-1 , 0
  4675.4     .05       0  4883.6     .04       0 4952.75     .04       0
 5047.25     .04       0  5069.9     .08       0
#XS Ineff= 2 ,-1
 5112.72 5321.98  105.31  5914.3 6694.33  105.88
Permanent Ineff=
       F       F
Bank Sta=4952.75,5047.25
XS Rating Curve= 0
Exp/Cntr=.5,.3

Type RM Length L Ch R = 1 ,3363.9  ,56.5,56.9,57.4
BEGIN DESCRIPTION:
Mauna Loa - 3
Formerly E141-00-00-02
END DESCRIPTION:
XS GIS Cut Line= 6
      3063950.64     13888002.99       3063360.2     13887631.82
       3063206.7     13887560.46      3062974.95     13887513.41
      3062332.78     13887635.91      3061737.55     13888087.93
#Sta/Elev= 30
  4218.7  106.42  4378.7  104.27  4538.7  103.54  4574.3   104.4  4690.4  103.12
  4904.9  104.65  4932.8  104.77  4948.7  103.32  4969.8   98.49  4988.9   92.87
  4996.6   89.62  4999.9   89.38  5003.8    89.7  5043.2  104.04  5053.8   104.8
  5092.4  104.44  5226.9  103.28  5276.9  104.72  5483.4  105.04  5513.4  103.55
  5583.4  105.27  6057.1  105.68  6167.1  103.71  6217.1  104.97  6287.1  104.59
  6387.1   105.9  6507.1  103.43  6557.1  104.85  6667.1  104.53  6724.5  106.25
#Mann= 5 ,-1 , 0
  4218.7     .05       0  4904.9     .04       0  4932.8     .04       0
  5053.8     .04       0  5092.4     .08       0
#XS Ineff= 3 ,-1
  4218.7 4932.82  104.77 5142.44 5286.52  104.43 6060.74 6713.97  105.68
Permanent Ineff=
       F       F       F
Bank Sta=4932.8,5053.8
XS Rating Curve= 0
Exp/Cntr=.5,.3

Type RM Length L Ch R = 3 ,3335.4  ,,,
BEGIN DESCRIPTION:
MAUNA LOA
Structure ID: E141-00-00-02
END DESCRIPTION:
Bridge Culvert--1,0,-1,-1, 0
Deck Dist Width WeirC Skew NumUp NumDn MinLoCord MaxHiCord MaxSubmerge Is_Ogee
10,36.9,2.6,0, 64, 64, , , .95, 0, 1,1,,
  4218.7  4298.7  4338.7  4378.7  4458.7  4538.7  4568.7  4574.3  4681.4  4690.4
  4752.6  4763.9  4803.7  4812.6  4853.7  4864.2  4889.7  4904.9 4921.99  4922.1
 4922.21    4929  4932.8  4948.7 4959.31  4959.4  4969.8  4974.8  4985.9  4988.9
  4994.9  4995.9  4996.6  4999.9  5003.8  5005.1  5010.9  5020.4  5021.9 5035.29
  5035.4  5043.2  5053.8  5066.3  5070.7 5072.89    5073 5073.11  5092.4  5106.6
  5146.5  5155.3  5177.1  5196.9  5201.4  5226.4  5226.9  5276.9  5323.4  5483.4
  5513.4  5543.4  5573.4  5668.7
  106.43  105.45  105.44  104.28  104.25  103.55   104.4  104.41  103.24  103.14
  103.91  103.97  104.16  104.19  104.33   104.4  104.57  104.67  104.74  107.56
  107.56  107.58  107.59  107.62  107.65  107.65  107.67  107.68  107.71  107.72
  107.74  107.74  107.74  107.75  107.76  107.77  107.78  107.81  107.81  107.85
  107.85  107.86  107.89  107.92  107.89  107.88  107.88  104.64  104.46  104.46
  104.45  104.25  103.76  103.46   103.4   103.5  103.29  104.73  104.86  105.02
  103.54  103.61  105.01  105.84
                                                                                
                                                                                
                                           101.3  101.32  101.33  101.36  101.37
  101.39  101.39  101.39   101.4  101.41  101.42  101.43  101.46  101.46   101.5
                                                                                
                                                                                
                                
  4218.7  4298.7  4338.7  4378.7  4458.7  4538.7  4568.7  4574.3  4681.4  4690.4
  4752.6  4763.9  4803.7  4812.6  4853.7  4864.2  4889.7  4904.9 4921.99  4922.1
 4922.21    4929  4932.8  4948.7 4959.31  4959.4  4969.8  4974.8  4985.9  4988.9
  4994.9  4995.9  4996.6  4999.9  5003.8  5005.1  5010.9  5020.4  5021.9 5035.29
  5035.4  5043.2  5053.8  5066.3  5070.7 5072.89    5073 5073.11  5092.4  5106.6
  5146.5  5155.3  5177.1  5196.9  5201.4  5226.4  5226.9  5276.9  5323.4  5483.4
  5513.4  5543.4  5573.4  5668.7
  106.43  105.45  105.44  104.28  104.25  103.55   104.4  104.41  103.24  103.14
  103.91  103.97  104.16  104.19  104.33   104.4  104.57  104.67  104.74  107.56
  107.56  107.58  107.59  107.62  107.65  107.65  107.67  107.68  107.71  107.72
  107.74  107.74  107.74  107.75  107.76  107.77  107.78  107.81  107.81  107.85
  107.85  107.86  107.89  107.92  107.89  107.88  107.88  104.64  104.46  104.46
  104.45  104.25  103.76  103.46   103.4   103.5  103.29  104.73  104.86  105.02
  103.54  103.61  105.01  105.84
                                                                                
                                                                                
                                           101.3  101.32  101.33  101.36  101.37
  101.39  101.39  101.39   101.4  101.41  101.42  101.43  101.46  101.46   101.5
                                                                                
                                                                                
                                
Pier Skew, UpSta & Num, DnSta & Num=  ,4995.9, 2 ,4995.9, 2 , 0 , 0 , 0 ,,
     2.5     2.5
   88.59  102.39
     2.5     2.5
   87.91  101.71
BR Coef= 1 , 1 , 0 ,1.25, 0 ,,,.8,0,2,0,
WSPro=,,,, 1 ,,,, 0 ,,,, 0 ,,,,-1 ,-1 ,-1 , 0 , 0 , 0 , 0 , 0
BC Design=,, 0 ,, 0 ,,,,,,

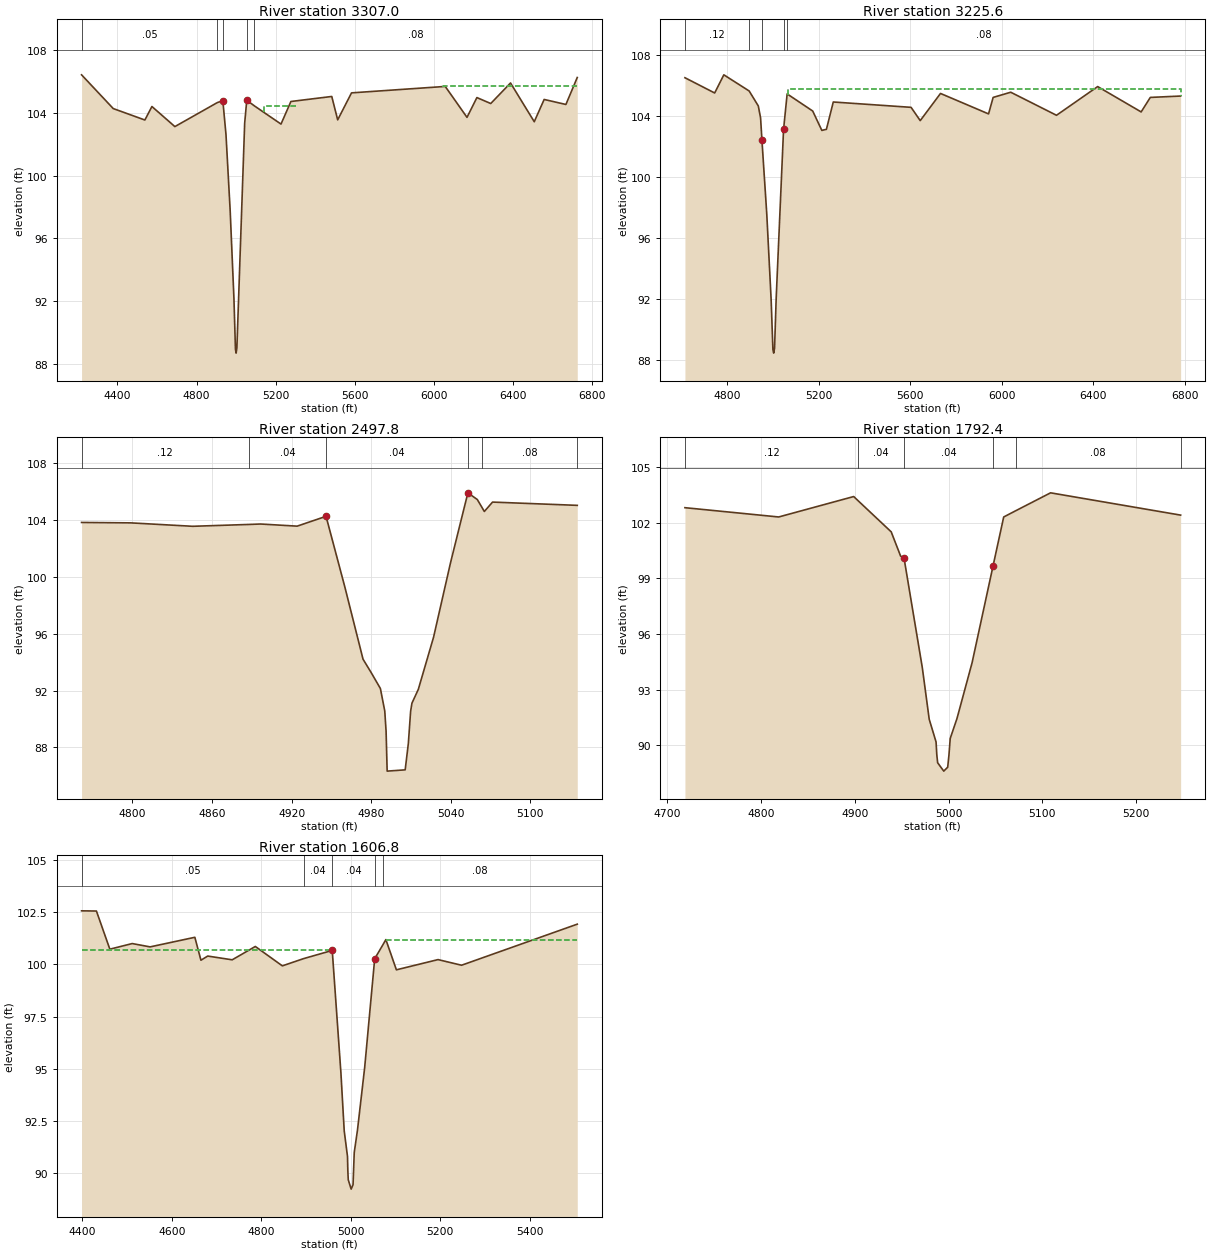
Type RM Length L Ch R = 1 ,3307.0  ,81.35,81.35,81.35
BEGIN DESCRIPTION:
Mauna Loa - 2
Formerly E141-00-00-02
END DESCRIPTION:
XS GIS Cut Line= 6
      3063969.64     13887953.04       3063379.2     13887581.87
       3063225.7     13887510.51      3062993.95     13887463.46
      3062351.78     13887585.96      3061756.55     13888037.98
#Sta/Elev= 30
  4218.7  106.42  4378.7  104.27  4538.7  103.54  4574.3   104.4  4690.4  103.12
  4904.9  104.65  4932.8  104.77  4948.7  102.62  4969.8   97.79  4988.9   92.17
  4996.6   88.92  4999.9   88.68  5003.8      89  5043.2  103.34  5053.8   104.8
  5092.4  104.44  5226.9  103.28  5276.9  104.72  5483.4  105.04  5513.4  103.55
  5583.4  105.27  6057.1  105.68  6167.1  103.71  6217.1  104.97  6287.1  104.59
  6387.1   105.9  6507.1  103.43  6557.1  104.85  6667.1  104.53  6724.5  106.25
#Mann= 5 ,-1 , 0
  4218.7     .05       0  4904.9     .04       0  4932.8     .04       0
  5053.8     .04       0  5092.4     .08       0
#XS Ineff= 3 ,-1
  4218.7  4932.8  104.77 5139.44 5301.96  104.44 6047.18 6727.14  105.68
Permanent Ineff=
       F       F       F
Bank Sta=4932.8,5053.8
XS Rating Curve= 0
Exp/Cntr=.5,.3

Type RM Length L Ch R = 1 ,3225.6  ,714.45,727.8,736.37
BEGIN DESCRIPTION:
Mauna Loa - 1
Formerly Cross Section xs02.5
END DESCRIPTION:
XS GIS Cut Line= 6
      3063697.62      13887602.1      3063403.73     13887501.47
      3063260.92     13887434.72      3062826.37     13887375.08
      3062316.33     13887459.01      3061754.67     13887944.59
#Sta/Elev= 30
  4616.2  106.49  4746.2  105.49  4786.2  106.68    4897  105.62  4936.8  104.64
  4946.8  103.86 4952.75  102.39 4973.85   97.56 4992.95   91.94 5000.65   88.69
 5004.05   88.45 5007.85   88.77 5014.95   92.03 5047.25  103.11  5062.9  105.43
  5174.5  104.31  5214.5  103.04  5234.5  103.11  5264.5   104.9  5604.5  104.55
  5644.5  103.68  5733.1  105.46  5943.1  104.12  5963.1   105.2    6040  105.54
    6240  104.03    6420  105.91    6610  104.25    6650   105.2  6782.5  105.29
#Mann= 5 ,-1 , 0
  4616.2     .12       0    4897     .04       0 4952.75     .04       0
 5047.25     .04       0  5062.9     .08       0
#XS Ineff= 2 , 0
                         5066.82          105.74
Permanent Ineff=
       F       F
Bank Sta=4952.75,5047.25
XS Rating Curve= 0
Exp/Cntr=.3,.1

Type RM Length L Ch R = 1 ,2497.8  ,743.39,705.4,667.86
BEGIN DESCRIPTION:
Cross Section xs02
Located At: US PHILLIPINE
END DESCRIPTION:
XS GIS Cut Line= 2
      3063915.31     13887002.26      3063617.72     13886775.92
#Sta/Elev= 27
  4761.6   103.8  4798.7  103.77  4845.4  103.53    4888  103.66  4896.6  103.69
  4924.2  103.54    4946  104.23  4960.1    99.3  4973.9    94.2  4980.1   93.25
    4987   92.14  4990.3   90.56  4991.3   89.13  4992.1   86.34  5005.7   86.43
  5008.1    88.3  5009.8   90.54  5010.8   91.11  5015.6   92.08  5027.1   95.74
  5039.9  100.97    5053  105.88  5060.1  105.41  5063.4  104.89  5065.4  104.57
  5071.6  105.23  5135.5     105
#Mann= 6 ,-1 , 0
  4761.6     .12       0    4888     .04       0    4946     .04       0
    5053     .04       0  5063.4     .08       0  5135.5      .2       0
Bank Sta=4946,5053
XS Rating Curve= 0
Exp/Cntr=.3,.1

Type RM Length L Ch R = 1 ,1792.4  ,188.58,185.65,152.58
BEGIN DESCRIPTION:
Philippine - 4
Formerly Cross Section xs01.7
END DESCRIPTION:
XS GIS Cut Line= 2
      3064264.25     13886209.92      3063735.53     13886206.07
#Sta/Elev= 23
  4718.8   102.8  4818.8   102.3  4898.8   103.4  4903.4  103.18  4938.8   101.5
  4948.8   100.2 4952.55  100.07 4971.95    94.2 4979.35   91.41 4986.65   90.19
 4987.45   89.49 4988.35   89.07 4994.85   88.62 4999.05   88.83 5000.35   89.46
 5001.75   90.38 5008.95   91.45 5025.05   94.45 5047.45   99.67  5058.8   102.3
  5071.4  102.63  5108.8   103.6  5247.5   102.4
#Mann= 6 ,-1 , 0
  4718.8     .12       0  4903.4     .04       0 4952.55     .04       0
 5047.45     .04       0  5071.4     .08       0  5247.5      .2       0
Bank Sta=4952.55,5047.45
XS Rating Curve= 0
Exp/Cntr=.5,.3

Type RM Length L Ch R = 1 ,1606.8  ,56.5,56.9,57
BEGIN DESCRIPTION:
Philippine - 3
Formerly E141-00-00-01
END DESCRIPTION:
XS GIS Cut Line= 5
      3064608.54     13885976.13      3064608.54     13885976.13
      3064099.54     13885994.22      3063865.36     13886067.76
      3063532.35     13886185.51
#Sta/Elev= 30
 4398.41  102.57  4431.6  102.56  4461.6  100.73  4511.6     101  4551.6  100.84
  4651.6   101.3  4665.2   100.2  4680.4   100.4  4735.1  100.22  4786.8  100.86
  4847.2   99.93  4895.1  100.28  4958.7  100.67  4978.1    94.8  4985.5   92.01
  4992.8   90.79  4993.6   90.09  4994.5   89.67    5001   89.22  5005.2   89.43
  5007.9   90.98  5015.1   92.05  5031.2   95.05  5053.6  100.27  5071.1  100.91
  5078.6  101.19  5102.1   99.74  5195.2  100.23  5247.8   99.96  5506.4  101.93
#Mann= 5 ,-1 , 0
 4398.41     .05       0  4895.1     .04       0  4958.7     .04       0
  5053.6     .04       0  5071.1     .08       0
#XS Ineff= 2 , 0
       0    4957   100.7 5078.59       0  101.19
Permanent Ineff=
       F       F
Bank Sta=4958.7,5053.6
XS Rating Curve= 0
Exp/Cntr=.5,.3