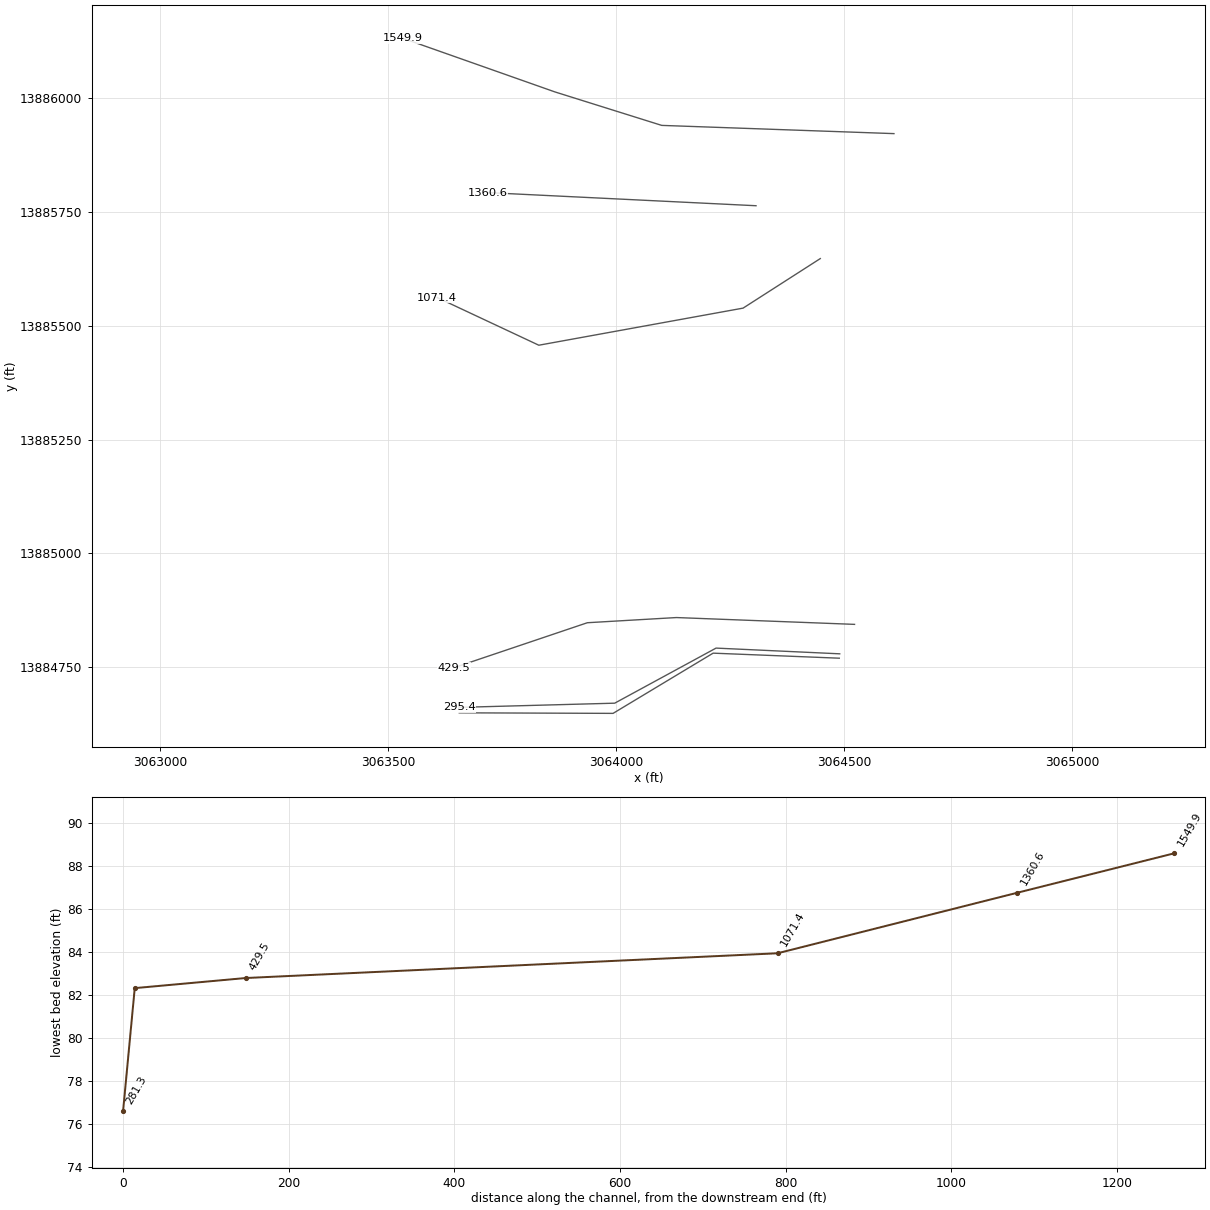
HEC-RAS study E141-00-00.prj: E141-00-00

--- E141-00-00.g01 (geometry) --- (continued)

Type RM Length L Ch R = 3 ,1578.3  ,,,
BEGIN DESCRIPTION:
PHILLIPPINE STREET
Structure ID: E141-00-00-01
END DESCRIPTION:
Bridge Culvert--1,0,-1,-1, 0
Deck Dist Width WeirC Skew NumUp NumDn MinLoCord MaxHiCord MaxSubmerge Is_Ogee
10,36.9,2.6,0, 62, 62, , , .95, 0, 1,1,,
  4391.6  4431.6  4461.6  4511.6  4551.6  4651.6  4665.2  4680.4  4695.7  4735.1
  4755.7  4771.5  4786.8  4820.8 4840.49  4840.6 4840.71  4847.2  4861.4  4895.1
  4896.9  4905.3  4956.6  4958.7 4967.11  4967.2  4978.1  4985.5  4992.8  4993.6
  4994.5  5000.6    5001  5005.2  5006.5  5007.9  5015.1  5031.2 5043.09  5043.2
  5053.6  5057.4  5071.1  5078.6  5102.1  5105.3  5111.2  5156.4  5159.1 5169.29
  5169.4 5169.51  5195.2  5209.1  5247.8  5257.9  5289.5  5436.4  5506.4  5556.4
  5626.4  5652.7
   102.6  102.59  100.76  101.03  100.87  101.33  100.23  100.43  100.39  100.26
  100.52  100.88  101.06  101.45  101.45  103.75  103.75  103.75  103.75  103.77
  103.77  103.77  103.82  103.82  103.84  103.84  103.85  103.87  103.88  103.88
  103.88  103.89  103.89   103.9   103.9   103.9  103.91  103.93  103.94  103.94
  103.96  103.96  103.97  103.98     104     104     104  104.04  104.04  104.06
  104.06  101.76  101.82  101.85  102.03  102.08     101  101.37  101.96  101.03
  103.23  103.32
                                                                                
                                                                                
                                           98.03   98.05   98.07   98.08   98.08
   98.08   98.09   98.09    98.1    98.1    98.1   98.11   98.13   98.14
                                                                                
                                                                                
                
  4391.6  4431.6  4461.6  4511.6  4551.6  4651.6  4665.2  4680.4  4695.7  4735.1
  4755.7  4771.5  4786.8  4820.8 4840.49  4840.6 4840.71  4847.2  4861.4  4895.1
  4896.9  4905.3  4956.6  4958.7 4967.11  4967.2  4978.1  4985.5  4992.8  4993.6
  4994.5  5000.6    5001  5005.2  5006.5  5007.9  5015.1  5031.2 5043.09  5043.2
  5053.6  5057.4  5071.1  5078.6  5102.1  5105.3  5111.2  5156.4  5159.1 5169.29
  5169.4 5169.51  5195.2  5209.1  5247.8  5257.9  5289.5  5436.4  5506.4  5556.4
  5626.4  5652.7
   102.6  102.59  100.76  101.03  100.87  101.33  100.23  100.43  100.39  100.26
  100.52  100.88  101.06  101.45  101.45  103.75  103.75  103.75  103.75  103.77
  103.77  103.77  103.82  103.82  103.84  103.84  103.85  103.87  103.88  103.88
  103.88  103.89  103.89   103.9   103.9   103.9  103.91  103.93  103.94  103.94
  103.96  103.96  103.97  103.98     104     104     104  104.04  104.04  104.06
  104.06  101.76  101.82  101.85  102.03  102.08     101  101.37  101.96  101.03
  103.23  103.32
                                                                                
                                                                                
                                           98.03   98.05   98.07   98.08   98.08
   98.08   98.09   98.09    98.1    98.1    98.1   98.11   98.13   98.14
                                                                                
                                                                                
                
Pier Skew, UpSta & Num, DnSta & Num=  ,4985.5, 2 ,4985.5, 2 , 0 , 0 , 0 ,,
     2.5     2.5
   90.83   99.07
     2.5     2.5
   90.27   98.51
BR Coef= 1 , 1 , 0 ,1.25, 0 ,,,.8,0,2,0,
WSPro=,,,, 1 ,,,, 0 ,,,, 0 ,,,,-1 ,-1 ,-1 , 0 , 0 , 0 , 0 , 0
BC Design=,, 0 ,, 0 ,,,,,,

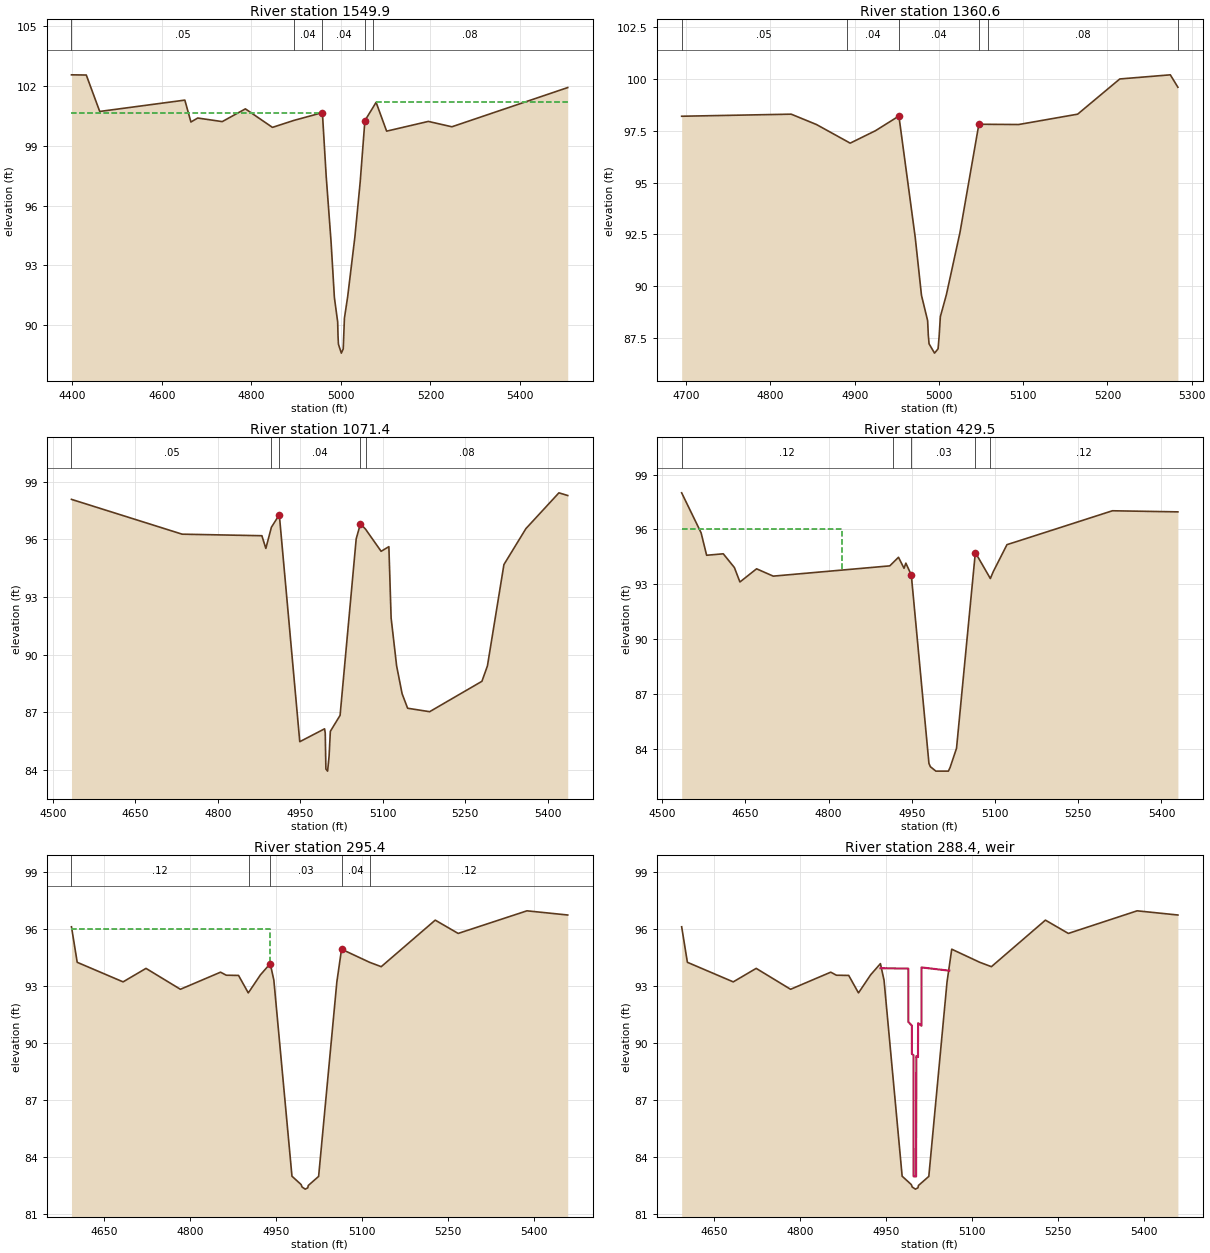
Type RM Length L Ch R = 1 ,1549.9  ,189.25,189.25,189.25
BEGIN DESCRIPTION:
Philippine - 2
Formerly E141-00-00-01
END DESCRIPTION:
XS GIS Cut Line= 5
      3064608.82     13885922.27      3064608.82     13885922.27
      3064099.82     13885940.35      3063865.64     13886013.89
      3063532.73     13886131.57
#Sta/Elev= 30
 4398.53  102.57  4431.6  102.56  4461.6  100.73  4651.6   101.3  4665.2   100.2
  4680.4   100.4  4735.1  100.22  4786.8  100.86  4847.2   99.93  4895.1  100.28
  4958.7  100.67 4967.11    97.5  4978.1   94.17  4985.5   91.38  4992.8   90.16
  4993.6   89.46  4994.5   89.04    5001   88.59  5005.2    88.8  5007.9   90.35
  5015.1   91.42  5031.2   94.42 5043.09   97.19  5053.6  100.27  5071.1  100.91
  5078.6  101.19  5102.1   99.74  5195.2  100.23  5247.8   99.96  5506.4  101.93
#Mann= 5 ,-1 , 0
 4398.53     .05       0  4895.1     .04       0  4958.7     .04       0
  5053.6     .04       0  5071.1     .08       0
#XS Ineff= 2 , 0
       0 4958.56  100.67 5078.62       0  101.19
Permanent Ineff=
       F       F
Bank Sta=4958.7,5053.6
XS Rating Curve= 0
Exp/Cntr=.5,.3

Type RM Length L Ch R = 1 ,1360.6  ,273.66,289.2,314.88
BEGIN DESCRIPTION:
Philippine - 1
Formerly Cross Section xs01.5
END DESCRIPTION:
XS GIS Cut Line= 2
      3064306.54     13885763.87      3063718.22     13885792.71
#Sta/Elev= 25
  4694.7    98.2  4824.7    98.3  4854.7    97.8  4890.8   96.99  4894.7    96.9
  4924.7    97.5 4952.55   98.21 4971.95   92.34 4979.35   89.55 4986.65   88.33
 4987.45   87.63 4988.35   87.21 4994.85   86.76 4999.05   86.97 5000.35    87.6
 5001.75   88.52 5008.95   89.59 5025.05   92.59 5047.45   97.81  5058.5   97.81
  5094.7    97.8  5164.7    98.3  5214.7     100  5274.7   100.2  5283.7    99.6
#Mann= 6 ,-1 , 0
  4694.7     .05       0  4890.8     .04       0 4952.55     .04       0
 5047.45     .04       0  5058.5     .08       0  5283.7      .2       0
Bank Sta=4952.55,5047.45
XS Rating Curve= 0
Exp/Cntr=.3,.1

Type RM Length L Ch R = 1 ,1071.4  ,647.99,641.9,628.3
BEGIN DESCRIPTION:
Cross Section xs01 **See Note**
Located At: DS PHILLIPINE
END DESCRIPTION:
XS GIS Cut Line= 4
      3064447.37     13885647.78      3064278.15     13885538.97
      3063830.43     13885457.48      3063607.76     13885562.11
#Sta/Elev= 30
    4534   98.08  4735.2   96.27  4880.2   96.19  4887.4   95.53  4897.5   96.63
  4911.9   97.28  4949.1   85.48  4994.2   86.15  4995.4   85.93  4996.6   84.06
  4999.7   83.95  5002.4   84.73  5004.7   86.02  5022.4   86.85  5051.7   96.03
  5059.4   96.81  5068.7   96.53    5097   95.38  5111.1   95.62  5115.2   91.91
  5125.2   89.42  5135.2   87.97  5145.2   87.22  5185.2   87.04  5280.3   88.62
  5290.3   89.42  5320.3   94.69  5360.3   96.56  5420.3   98.42  5436.3   98.28
#Mann= 5 ,-1 , 0
    4534     .05       0  4897.5     .04       0  4911.9     .04       0
  5059.4     .04       0  5068.7     .08       0
#XS Ineff= 2 , 0
       0                  5059.4       0   96.81
Permanent Ineff=
       F       F
Bank Sta=4911.9,5059.4
XS Rating Curve= 0
Exp/Cntr=.3,.1

Type RM Length L Ch R = 1 ,429.5   ,133.8,134.1,135
BEGIN DESCRIPTION:
Cross Section xs_c
Located At: 2ND DS PHILLIPINE
END DESCRIPTION:
XS GIS Cut Line= 4
      3064522.46      13884844.3      3064132.04     13884859.28
      3063936.83     13884847.91       3063645.1     13884749.33
#Sta/Elev= 29
  4535.4      98  4570.4   95.82  4580.4   94.59  4610.4   94.67  4630.4   93.92
  4640.4   93.13  4670.4   93.85  4700.4   93.45  4910.1   94.01  4910.4   94.01
  4916.1   94.18  4926.1   94.48  4936.1   93.88  4939.4   94.16  4949.2   93.51
    4981   83.22  4983.6   83.04  4993.5    82.8    5016    82.8    5019   82.99
  5030.7   84.05  5064.6   94.74  5090.3   93.39  5091.7   93.32  5096.8   93.69
  5121.6   95.17  5143.4   95.38  5311.6   97.02  5429.6   96.96
#Mann= 5 ,-1 , 0
  4535.4     .12       0  4916.1     .04       0  4949.2     .03       0
  5064.6     .04       0  5090.3     .12       0
#XS Ineff= 2 , 0
       0    4825      96               0
Permanent Ineff=
       F       F
Bank Sta=4949.2,5064.6
XS Rating Curve= 0
Exp/Cntr=.7,.5

Type RM Length L Ch R = 1 ,295.4   ,14.5,14.1,14
BEGIN DESCRIPTION:
Cross Section xs_b
Located At: 3RD DS PHILLIPINE
END DESCRIPTION:
XS GIS Cut Line= 4
      3064489.98     13884779.61       3064218.9     13884792.18
      3063996.71     13884671.19      3063655.74     13884661.95
#Sta/Elev= 28
  4593.2   96.14  4603.2   94.27  4683.2   93.24  4723.2   93.95  4783.2   92.85
  4853.2   93.75  4863.2   93.59  4884.6   93.58  4901.6   92.66    4903   92.72
  4922.8   93.61  4939.9    94.2  4946.2   93.33  4977.8   83.01  4993.8   82.57
  4995.4   82.44    5001   82.33  5005.4    82.4  5006.2   82.52  5024.3      83
  5056.1   93.24  5064.3   94.96  5113.2   94.27  5133.5   94.04  5227.7   96.49
  5267.7   95.79  5387.7   96.98  5458.8   96.76
#Mann= 5 ,-1 , 0
  4593.2     .12       0    4903     .04       0  4939.9     .03       0
  5064.3     .04       0  5113.2     .12       0
#XS Ineff= 2 , 0
       0  4939.9      96  5064.3       0   94.96
Permanent Ineff=
       F       F
Bank Sta=4939.9,5064.3
XS Rating Curve= 0
Exp/Cntr=.7,.5

Type RM Length L Ch R = 5 ,288.4   ,,,
IW Pilot Flow=0
#Inline Weir SE= 14
    4940   93.96 4988.51   93.94 4988.57   91.13 4994.67   90.94 4994.71   89.45
 4997.72   89.38 4997.78      83 5002.23      83 5002.44   89.33 5005.42   89.28
 5005.58   91.07 5011.49   90.93 5011.55      94    5060   93.83
IW Dist,WD,Coef,Skew,MaxSub,Min_El,Is_Ogee,SpillHt,DesHd
6.5,1,3,0,.95,, 0 ,,,0,0,

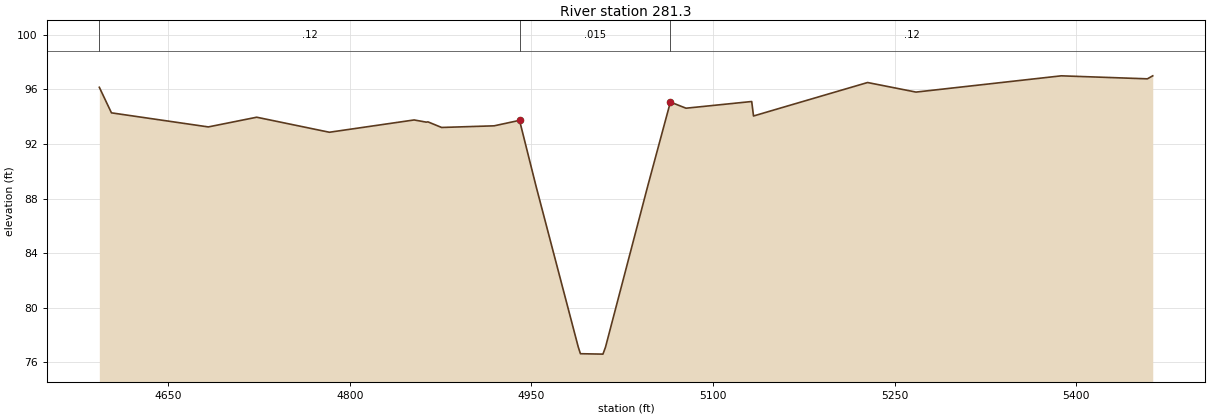
Type RM Length L Ch R = 1 ,281.3   ,0,0,0
BEGIN DESCRIPTION:
Cross Section xs_a
END DESCRIPTION:
XS GIS Cut Line= 4
        3064489.       13884770.     3064212.465     13884781.07
     3063993.132     13884648.79        3063656.       13884650.
#Sta/Elev= 27
  4593.2   96.14  4603.2   94.27  4683.2   93.24  4723.2   93.95  4783.2   92.85
  4853.2   93.75  4863.2   93.59  4864.6   93.61  4875.9    93.2 4919.25   93.32
 4940.25   93.72 4953.95   88.88 4988.75   77.13 4990.55   76.64 5009.15   76.61
 5011.25   77.12 5046.25   88.95 5064.85   95.06 5077.75   94.61    5132    95.1
  5133.5   94.04  5154.2   94.58  5227.7   96.49  5267.7   95.79  5387.7   96.98
  5458.8   96.76 5463.23   96.98
#Mann= 3 ,-1 , 0
  4593.2     .12       0 4940.25    .015       0 5064.85     .12       0
Bank Sta=4940.25,5064.85
XS Rating Curve= 0
Exp/Cntr=.7,.5

Chan Stop Cuts=-1